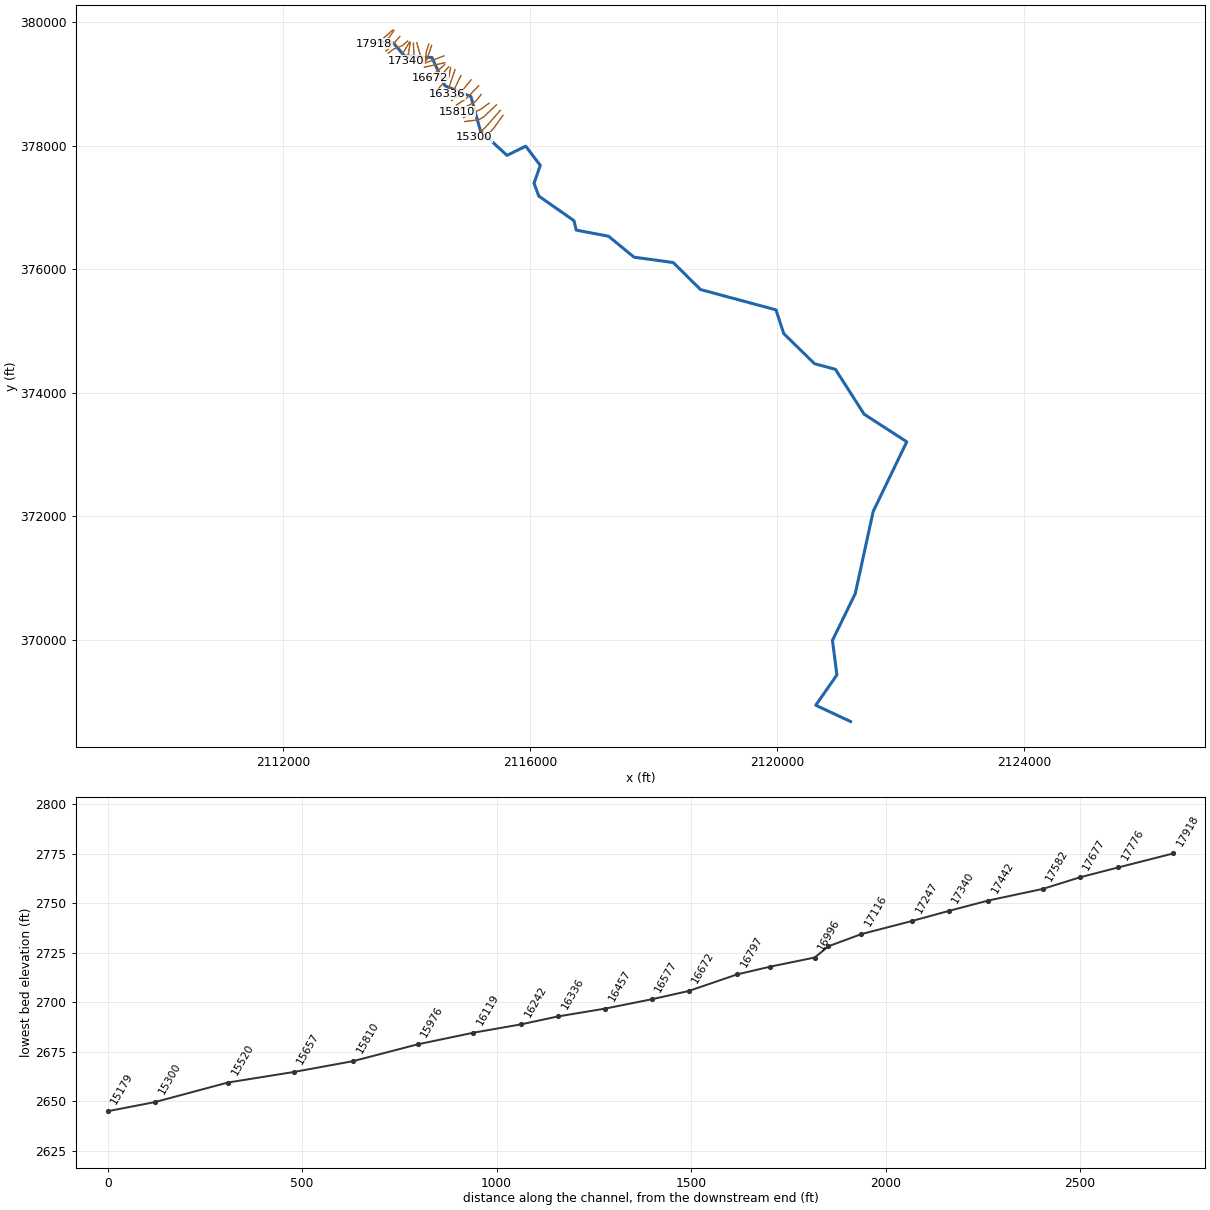
--- ROARINGCK.prj (project) ---

Proj Title=ROARINGCK
Current Plan=p01
Default Exp/Contr=0.3,0.1
English Units
Geom File=g01
Flow File=f01
Plan File=p01
Y Axis Title=Elevation
X Axis Title(PF)=Main Channel Distance
X Axis Title(XS)=Station
BEGIN DESCRIPTION:
Stream Name- ROARINGCK
Flood Zone: Zone A
Greenbrier County, WV
County-Wide Study
WVDHSEM-2018-3, Flood Risk Project
HEC-RAS Version: 5.0.7
General Notes:
For the Hydrology Regression was used.
END DESCRIPTION:
DSS Export Rating Curves= 0
DSS Export Rating Curve Sorted= 0
DSS Export Volume Flow Curves= 0
DXF Filename=ROARINGCK.G2.
DXF OffsetX= 0
DXF OffsetY= 0
DXF ScaleX= 1
DXF ScaleY= 10

--- ROARINGCK.p01 (plan) ---

Plan Title=Floodplain
Program Version=5.07
Short Identifier=Floodplain
Geom File=g01
Flow File=f01
Subcritical Flow
K Sum by GR= 0
Std Step Tol= 0.01
Critical Tol= 0.01
Num of Std Step Trials= 20
Max Error Tol= 0.3
Flow Tol Ratio= 0.001
Split Flow NTrial= 30
Split Flow Tol= 0.02
Split Flow Ratio= 0.02
Log Output Level= 0
Friction Slope Method= 1
Unsteady Friction Slope Method= 2
Unsteady Bridges Friction Slope Method= 1
Parabolic Critical Depth
Global Vel Dist= 0 , 0 , 0
Global Log Level= 0
CheckData=True
Encroach Param=-1 ,0,0, 0
Computation Interval=1MIN
Output Interval=1HOUR
Instantaneous Interval=1HOUR
Mapping Interval=1HOUR
Computation Time Step Use Courant=        0
Computation Time Step Use Time Series=    0
Computation Time Step Count To Double=0
Computation Time Step Max Doubling=0
Computation Time Step Max Halving=0
Computation Time Step Residence Courant=0
Run HTab= 0
Run UNet= 0
Run Sediment= 0
Run PostProcess= 0
Run WQNet= 0
Run RASMapper= 0
UNET Theta= 1
UNET Theta Warmup= 1
UNET ZTol= 0.02
UNET ZSATol= 0.02
UNET MxIter= 20
UNET Max Iter WO Improvement= 0
UNET MaxInSteps= 0
UNET DtIC= 0
UNET DtMin= 0
UNET MaxCRTS= 20
UNET WFStab= 2
UNET SFStab= 1
UNET WFX= 1
UNET SFX= 1
UNET 1D Methodology=Finite Difference
UNET DSS MLevel= 4
UNET Pardiso=0
UNET DZMax Abort= 100
UNET Use Existing IB Tables=-1
UNET Froude Reduction=False
UNET Froude Limit= 0.8
UNET Froude Power= 4
UNET D1 Cores= 0
UNET D2 Coriolis=0
UNET D2 Cores= 0
UNET D2 Theta= 1
UNET D2 Theta Warmup= 1
UNET D2 Z Tol= 0.01
UNET D2 Volume Tol= 0.01
UNET D2 Max Iterations= 20
UNET D2 Equation= 0
UNET D2 RampUpFraction=0.1
UNET D2 TimeSlices= 1
UNET D2 BCVolumeCheck=0
UNET D1D2 MaxIter= 0
UNET D1D2 ZTol=0.01
UNET D1D2 QTol=0.1
UNET D1D2 MinQTol=1
Write IC File= 0
Write IC File at Fixed DateTime=0
Write IC File at Sim End=0
Echo Input=False
Echo Parameters=False
Echo Output=False
Write Detailed= 0
HDF Write Warmup=0
HDF Write Time Slices=0
HDF Flush=0
HDF Face Node Velocities=0
HDF Compression= 1
HDF Chunk Size= 1
HDF Spatial Parts= 1
HDF Use Max Rows=0
HDF Fixed Rows= 1
Calibration Method= 0
Calibration Iterations= 20
Calibration Max Change=0.05
Calibration Tolerance=0.2
Calibration Maximum=1.5
Calibration Minimum=0.5
Calibration Optimization Method= 1
WQ AD Non Conservative
WQ ULTIMATE=-1
WQ Max Comp Step=1HOUR
WQ Output Interval=15MIN
WQ Output Selected Increments= 0
WQ Output face flow=0
WQ Output face velocity=0
WQ Output face area=0
WQ Output face dispersion=0
WQ Output cell volume=0
WQ Output cell surface area=0
WQ Output cell continuity=0
WQ Output cumulative cell continuity=0
WQ Output face conc=0
WQ Output face dconc_dx=0
WQ Output face courant=0
WQ Output face peclet=0
WQ Output face adv mass=0
WQ Output face disp mass=0
WQ Output cell mass=0
WQ Output cell source sink temp=0
WQ Output nsm pathways=0
WQ Output nsm derived pathways=0
WQ Output MaxMinRange=-1
WQ Daily Max Min Mean=-1
WQ Daily Range=0
WQ Daily Time=0
WQ Create Restart=0
WQ Fixed Restart=0
WQ System Summary=0
WQ Write To DSS=0
WQ Use Fixed Temperature=0
Sorting and Armoring Iterations= 10
XS Update Threshold= 0.02
Bed Roughness Predictor= 0
Hydraulics Update Threshold= 0.02
Energy Slope Method= 1
Volume Change Method= 1
Sediment Retention Method= 0
XS Weighting Method= 0
Number of US Weighted Cross Sections= 1
Number of DS Weighted Cross Sections= 1
Upstream XS Weight=0
Main XS Weight=1
Downstream XS Weight=0
Number of DS XS's Weighted with US Boundary= 1
Upstream Boundary Weight= 1
Weight of XSs Associated with US Boundary= 0
Number of US XS's Weighted with DS Boundary= 1
Downstream Boundary Weight= 0.5
Weight of XSs Associated with DS Boundary= 0.5
Percentile Method= 0
Sediment Output Level= 3
Mass or Volume Output= 0
Output Increment Type= 1
Profile and TS Output Increment= 1
XS Output Flag= 0
XS Output Increment= 10
Write Gradation File= 0
Read Gradation Hotstart= 0
Write HDF5 File= 1
Write Binary Output= 1
Write DSS Sediment File= 0
SV Curve= 0
Specific Gage Flag= 0

--- ROARINGCK.f01 (steady flow) ---

Flow Title=Flow
Program Version=5.07
Number of Profiles= 6
Profile Names=f1p,f10p,f4p,f2p,f02p,f1pplus
River Rch & RM=BURNSRN,Main            ,9203
     572     302     402     484     799     846
River Rch & RM=BURNSRN,Main            ,7195
     649     345     457     550     905     960
River Rch & RM=BURNSRN,Main            ,4526
    1220     661     867    1040    1670    1800
River Rch & RM=BURNSRNT1,Main            ,2875
     504     265     353     426     705     745
River Rch & RM=BURNSRNT1,Main            ,2198
     669     356     472     568     932     990
River Rch & RM=CLBRSNCKT1,Main            ,2948
     116    57.4    78.7    96.5     166     171
River Rch & RM=CLBRSNCKT1,Main            ,2280
     138    69.1    94.4     116     198     210
River Rch & RM=CLBRSNCKT1,Main            ,1216
     156    78.2     107     130     223     230
River Rch & RM=CLBRSNCKT1,Main            ,243
     178    89.6     122     149     253     300
River Rch & RM=CLBRSNCKT2,Main            ,5369
     223     114     154     187     317     330
River Rch & RM=CLBRSNCKT2,Main            ,3799
     483     253     338     408     676     714
River Rch & RM=INDIANCK,Main            ,11519
     313     162     218     264     443     463
River Rch & RM=INDIANCK,Main            ,9807
     520     274     365     440     728     769
River Rch & RM=INDIANCK,Main            ,8108
     581     307     409     492     812     860
River Rch & RM=INDIANCK,Main            ,6227
     647     344     456     549     902     958
River Rch & RM=LTROARCK,Main            ,4000
     648     344     456     549     903     958
River Rch & RM=MLGNCKTR5,Main            ,7678
     581     307     409     492     812     860
River Rch & RM=MLGNCKTR5,Main            ,5118
     654     347     461     554     911     967
River Rch & RM=MLGNCKTR5,Main            ,2636
     728     388     514     617    1010    1080
River Rch & RM=ROARINGCK,Main            ,17918
     544     287     382     461     761     805
River Rch & RM=ROARINGCK,Main            ,16996
     613     325     431     519     855     906
River Rch & RM=ROARINGCK,Main            ,14906
     713     380     504     605     992    1060
River Rch & RM=ROARINGCK,Main            ,11661
     864     464     612     734    1200    1280
River Rch & RM=ROARINGCK,Main            ,8657
     964     520     685     820    1330    1430
River Rch & RM=ROARINGCK,Main            ,4987
    1570     861    1120    1340    2150    2320
Boundary for River Rch & Prof#=BURNSRN,Main            , 1
Up Type= 0
Dn Type= 3
Dn Slope=0.0012
Boundary for River Rch & Prof#=BURNSRN,Main            , 2
Up Type= 0
Dn Type= 3
Dn Slope=0.0012
Boundary for River Rch & Prof#=BURNSRN,Main            , 3
Up Type= 0
Dn Type= 3
Dn Slope=0.0012
Boundary for River Rch & Prof#=BURNSRN,Main            , 4
Up Type= 0
Dn Type= 3
Dn Slope=0.0012
Boundary for River Rch & Prof#=BURNSRN,Main            , 5
Up Type= 0
Dn Type= 3
Dn Slope=0.0012
Boundary for River Rch & Prof#=BURNSRN,Main            , 6
Up Type= 0
Dn Type= 3
Dn Slope=0.0012
Boundary for River Rch & Prof#=BURNSRNT1,Main            , 1
Up Type= 0
Dn Type= 3
Dn Slope=0.00496
Boundary for River Rch & Prof#=BURNSRNT1,Main            , 2
Up Type= 0
Dn Type= 3
Dn Slope=0.00496
Boundary for River Rch & Prof#=BURNSRNT1,Main            , 3
Up Type= 0
Dn Type= 3
Dn Slope=0.00496
Boundary for River Rch & Prof#=BURNSRNT1,Main            , 4
Up Type= 0
Dn Type= 3
Dn Slope=0.00496
Boundary for River Rch & Prof#=BURNSRNT1,Main            , 5
Up Type= 0
Dn Type= 3
Dn Slope=0.00496
Boundary for River Rch & Prof#=BURNSRNT1,Main            , 6
Up Type= 0
Dn Type= 3
Dn Slope=0.00496
Boundary for River Rch & Prof#=CLBRSNCKT1,Main            , 1
Up Type= 0
Dn Type= 3
Dn Slope=0.00848
Boundary for River Rch & Prof#=CLBRSNCKT1,Main            , 2
Up Type= 0
Dn Type= 3
Dn Slope=0.00848
Boundary for River Rch & Prof#=CLBRSNCKT1,Main            , 3
Up Type= 0
Dn Type= 3
Dn Slope=0.00848
Boundary for River Rch & Prof#=CLBRSNCKT1,Main            , 4
Up Type= 0
Dn Type= 3
Dn Slope=0.00848
Boundary for River Rch & Prof#=CLBRSNCKT1,Main            , 5
Up Type= 0
Dn Type= 3
Dn Slope=0.00848
Boundary for River Rch & Prof#=CLBRSNCKT1,Main            , 6
Up Type= 0
Dn Type= 3
Dn Slope=0.00848
Boundary for River Rch & Prof#=CLBRSNCKT2,Main            , 1
Up Type= 0
Dn Type= 3
Dn Slope=0.00274
Boundary for River Rch & Prof#=CLBRSNCKT2,Main            , 2
Up Type= 0
Dn Type= 3
Dn Slope=0.00274
Boundary for River Rch & Prof#=CLBRSNCKT2,Main            , 3
Up Type= 0
Dn Type= 3
Dn Slope=0.00274
Boundary for River Rch & Prof#=CLBRSNCKT2,Main            , 4
Up Type= 0
Dn Type= 3
Dn Slope=0.00274
Boundary for River Rch & Prof#=CLBRSNCKT2,Main            , 5
Up Type= 0
Dn Type= 3
Dn Slope=0.00274
Boundary for River Rch & Prof#=CLBRSNCKT2,Main            , 6
Up Type= 0
Dn Type= 3
Dn Slope=0.00274
Boundary for River Rch & Prof#=INDIANCK,Main            , 1
Up Type= 0
Dn Type= 3
Dn Slope=0.00176
Boundary for River Rch & Prof#=INDIANCK,Main            , 2
Up Type= 0
Dn Type= 3
Dn Slope=0.00176
Boundary for River Rch & Prof#=INDIANCK,Main            , 3
Up Type= 0
Dn Type= 3
Dn Slope=0.00176
Boundary for River Rch & Prof#=INDIANCK,Main            , 4
Up Type= 0
Dn Type= 3
Dn Slope=0.00176
Boundary for River Rch & Prof#=INDIANCK,Main            , 5
Up Type= 0
Dn Type= 3
Dn Slope=0.00176
Boundary for River Rch & Prof#=INDIANCK,Main            , 6
Up Type= 0
Dn Type= 3
Dn Slope=0.00176
Boundary for River Rch & Prof#=LTROARCK,Main            , 1
Up Type= 0
Dn Type= 3
Dn Slope=0.04436
Boundary for River Rch & Prof#=LTROARCK,Main            , 2
Up Type= 0
Dn Type= 3
Dn Slope=0.04436
Boundary for River Rch & Prof#=LTROARCK,Main            , 3
Up Type= 0
Dn Type= 3
Dn Slope=0.04436
Boundary for River Rch & Prof#=LTROARCK,Main            , 4
Up Type= 0
Dn Type= 3
Dn Slope=0.04436
Boundary for River Rch & Prof#=LTROARCK,Main            , 5
Up Type= 0
Dn Type= 3
Dn Slope=0.04436
Boundary for River Rch & Prof#=LTROARCK,Main            , 6
Up Type= 0
Dn Type= 3
Dn Slope=0.04436
Boundary for River Rch & Prof#=MLGNCKTR5,Main            , 1
Up Type= 0
Dn Type= 3
Dn Slope=0.0247
Boundary for River Rch & Prof#=MLGNCKTR5,Main            , 2
Up Type= 0
Dn Type= 3
Dn Slope=0.0247
Boundary for River Rch & Prof#=MLGNCKTR5,Main            , 3
Up Type= 0
Dn Type= 3
Dn Slope=0.0247
Boundary for River Rch & Prof#=MLGNCKTR5,Main            , 4
Up Type= 0
Dn Type= 3
Dn Slope=0.0247
Boundary for River Rch & Prof#=MLGNCKTR5,Main            , 5
Up Type= 0
Dn Type= 3
Dn Slope=0.0247
Boundary for River Rch & Prof#=MLGNCKTR5,Main            , 6
Up Type= 0
Dn Type= 3
Dn Slope=0.0247
Boundary for River Rch & Prof#=ROARINGCK,Main            , 1
Up Type= 0
Dn Type= 3
Dn Slope=0.01435
Boundary for River Rch & Prof#=ROARINGCK,Main            , 2
Up Type= 0
Dn Type= 3
Dn Slope=0.01435
Boundary for River Rch & Prof#=ROARINGCK,Main            , 3
Up Type= 0
Dn Type= 3
Dn Slope=0.01435
Boundary for River Rch & Prof#=ROARINGCK,Main            , 4
Up Type= 0
Dn Type= 3
Dn Slope=0.01435
Boundary for River Rch & Prof#=ROARINGCK,Main            , 5
Up Type= 0
Dn Type= 3
Dn Slope=0.01435
Boundary for River Rch & Prof#=ROARINGCK,Main            , 6
Up Type= 0
Dn Type= 3
Dn Slope=0.01435
DSS Import GetInterval= 0
DSS Import GetPeak= 0
DSS Import FillOption= 0

--- ROARINGCK.g01 (geometry) ---

Geom Title=Geometry
Program Version=5.07

River Reach=ROARINGCK       ,Main
Reach XY= 30
2113562.84966347379690.6979905372113780.57921487379663.115696609
2113963.07950604379451.4487971222114406.41260886379426.448847115
2114616.82951087378968.9487778692115038.07932454378793.532133952
2115192.24601096378236.8655963692115622.24613521 377841.44873628
2115924.74618638377990.1987668722116161.41270781377679.365399033
2116059.74591637377389.3656509522116137.24608946377181.865409777
2116706.41260204376784.365548611 2116743.4961893376631.032193869
2117267.24612606376531.8653974532117679.32929137376192.698752955
2118314.32933372376105.6155937762118755.99610129375668.532150358
 2119978.9126187375339.3654858622120103.91269678374955.198931366
2120602.38479695374467.6434760392120941.27388296374375.976664618
 2121406.2739372373649.3101389562122096.82931462373202.643381372
2121553.01281697  372075.01309072121262.22041956370743.135177031
2120893.20737803369985.6658914542120965.28400555 369426.93439737
2120623.06848264368935.6660229412121185.56834188368671.985447943

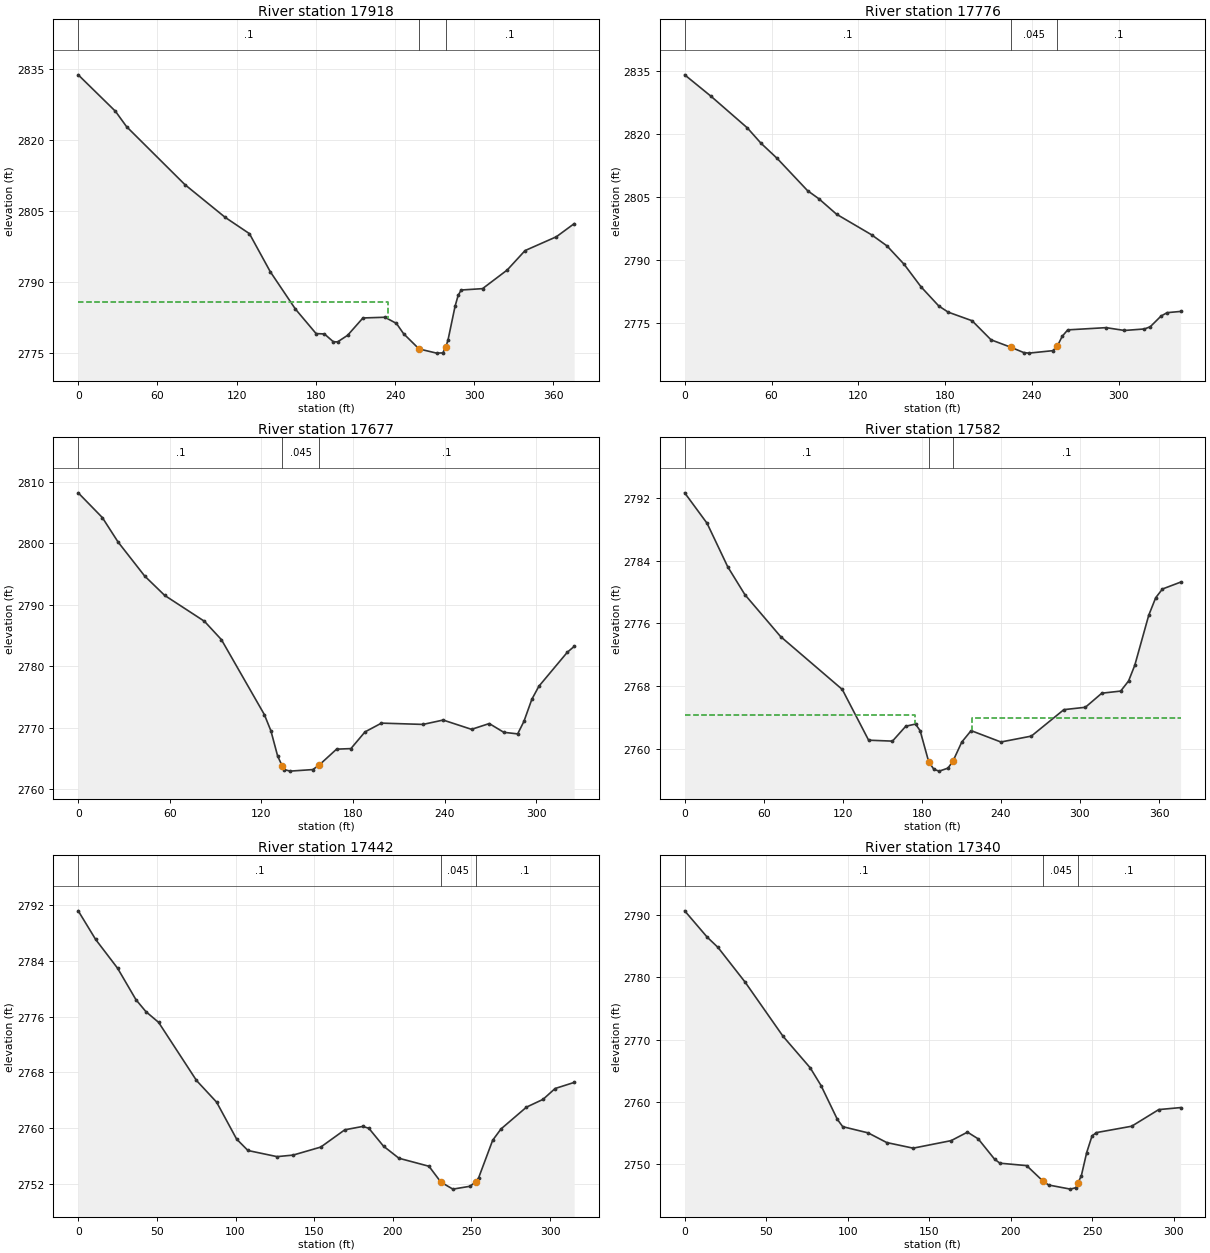
Type RM Length L Ch R = 1 ,17918   ,129.89,142.43,154.96
XS GIS Cut Line= 3
2113769.91552231379868.936807275 2113532.4156692379662.686891705
2113473.04045987379648.103587538
#Sta/Elev= 30
       0 2833.71    28.2 2826.03    36.6  2822.8    80.8 2810.58   111.4 2803.66
   129.7 2800.24   145.5 2792.22   164.5 2784.36   180.2 2779.18   186.5  2779.1
   193.3 2777.45   196.5 2777.43   204.1 2778.82   215.7 2782.47   232.4 2782.62
   241.1 2781.31   246.5 2779.15  258.222775.939   271.5 2775.06   276.2 2775.11
   278.5 2776.35   280.2  2777.9   285.5 2784.95   287.8 2787.21   290.1 2788.36
   306.3 2788.65     325 2792.58   338.5 2796.67   362.2 2799.58   375.7 2802.34
#Mann= 3 ,-1 , 0
       0      .1       0  258.22    .045       0   278.5      .1       0
#XS Ineff= 2 , 0
          234.75 2785.74
Permanent Ineff=
       F       F
Bank Sta=258.22,278.5
XS Rating Curve= 0 ,0
Exp/Cntr=0.3,0.1

Type RM Length L Ch R = 1 ,17776   ,109.55,98.93,88.3
XS GIS Cut Line= 4
2113791.99881145379865.290817201 2113695.1240052379727.790764108
2113691.99901146379616.3326537012113643.04044795379576.749071449
#Sta/Elev= 30
       0 2834.04    18.3 2828.92    43.3 2821.44    52.7 2817.81    63.9  2814.2
    84.9 2806.54    92.7 2804.62     105 2800.93   129.1 2796.07   139.8 2793.42
   151.6 2789.07   163.3 2783.71   175.6 2779.15   182.1 2777.69   198.6 2775.65
   211.7 2771.12   225.5 2769.34   234.3 2768.09   237.9 2767.96   254.3 2768.54
   257.4 2769.56   260.9 2771.97   264.7 2773.48   291.2 2774.01   303.9 2773.34
   317.7  2773.7   321.7 2774.22   329.2 2776.77   333.4 2777.57   342.7 2777.86
#Mann= 3 ,-1 , 0
       0      .1       0   225.5    .045       0   257.4      .1       0
Bank Sta=225.5,257.4
XS Rating Curve= 0 ,0
Exp/Cntr=0.3,0.1

Type RM Length L Ch R = 1 ,17677   ,102.04,94.66,87.29
XS GIS Cut Line= 3
2113885.74895203379766.3326817752113750.33222812379611.124330789
2113661.79073855379531.957494363
#Sta/Elev= 30
       0 2808.16    15.8 2804.14    26.1 2800.17    43.5 2794.65    56.6  2791.5
    82.7 2787.28    93.8  2784.3   121.9 2772.13   126.2 2769.49   130.6  2765.4
   133.7 2763.72     135  2763.2   138.7 2762.94   153.6 2763.19   157.6 2763.88
   169.2 2766.51   178.6  2766.6   187.8 2769.31   198.6 2770.74   225.8 2770.53
     239 2771.24   257.6 2769.73   269.2 2770.67   278.7 2769.25   287.8 2768.99
   291.9 2771.02   297.1 2774.62   301.7 2776.73   320.3 2782.25   324.8  2783.2
#Mann= 3 ,-1 , 0
       0      .1       0   133.7    .045       0   157.6      .1       0
Bank Sta=133.7,157.6
XS Rating Curve= 0 ,0
Exp/Cntr=0.3,0.1

Type RM Length L Ch R = 1 ,17582   ,130.37,140.53,150.69
XS GIS Cut Line= 4
2114012.83235928379693.4158328622113925.33220622379617.374318287
2113784.70715937379563.2077599472113698.24899897379495.499233946
#Sta/Elev= 30
       0 2792.67      17 2788.78    32.7 2783.22    45.7 2779.67    72.8 2774.32
   119.6 2767.57   139.6 2761.09   157.7 2760.97   167.8 2762.87   175.2 2763.15
   178.7  2762.3   185.2 2758.34   189.2 2757.36   193.2 2757.14   199.8 2757.52
   203.5 2758.37   210.3 2760.85   217.4 2762.31     240 2760.86   263.1 2761.61
   287.8 2764.99   304.1 2765.29   316.6 2767.09   330.9 2767.36   336.9 2768.65
   341.6 2770.65   352.2 2777.04   357.5 2779.28   362.6 2780.39   376.4 2781.27
#Mann= 3 ,-1 , 0
       0      .1       0   185.2    .045       0   203.5      .1       0
#XS Ineff= 2 , 0
          174.76  2764.3  217.77         2763.89
Permanent Ineff=
       F       F
Bank Sta=185.2,203.5
XS Rating Curve= 0 ,0
Exp/Cntr=0.3,0.1

Type RM Length L Ch R = 1 ,17442   ,95.92,101.58,107.25
XS GIS Cut Line= 2
2114043.04063222379675.7075349542113881.58229372 379404.87408711
#Sta/Elev= 30
       0 2791.17    11.1 2787.06      25 2782.95    36.7 2778.43    43.1  2776.7
    51.1 2775.18    75.2 2766.84      88 2763.73   100.7 2758.44   107.9  2756.8
   126.4 2755.92   136.6 2756.14   154.2 2757.29   169.5 2759.77   180.9 2760.25
   184.8 2759.98   194.1 2757.42   203.9 2755.69     223 2754.54   230.6 2752.26
   238.2 2751.26   249.1 2751.67  252.742752.298   254.6  2752.9   263.5 2758.27
   268.8 2759.89     285 2763.02   295.5 2764.13   303.2 2765.69   315.3 2766.56
#Mann= 3 ,-1 , 0
       0      .1       0   230.6    .045       0  252.74      .1       0
Bank Sta=230.6,252.74
XS Rating Curve= 0 ,0
Exp/Cntr=0.3,0.1

Type RM Length L Ch R = 1 ,17340   ,94.11,93.51,92.9
XS GIS Cut Line= 3
2114054.49894261379668.4158828712114011.79069471379406.957416281
 2113993.0407322379372.582485035
#Sta/Elev= 30
       0 2790.64    13.8 2786.42    20.4 2784.78    37.1 2779.19    60.3 2770.52
      77 2765.45    83.6 2762.62    93.6  2757.2    96.9 2756.02   112.5 2755.02
   123.9 2753.47   140.1 2752.57   163.4 2753.78   173.4 2755.14     180 2754.06
     190 2750.81   193.3 2750.16   209.7 2749.77   219.9 2747.24   223.2 2746.66
   236.5    2746   239.9 2746.23   241.1 2746.99   243.2 2748.12   246.5 2751.86
   249.8 2754.55   252.5 2755.07   274.1 2756.09   290.7 2758.76   304.1 2759.08
#Mann= 3 ,-1 , 0
       0      .1       0   219.9    .045       0   241.1      .1       0
Bank Sta=219.9,241.1
XS Rating Curve= 0 ,0
Exp/Cntr=0.3,0.1

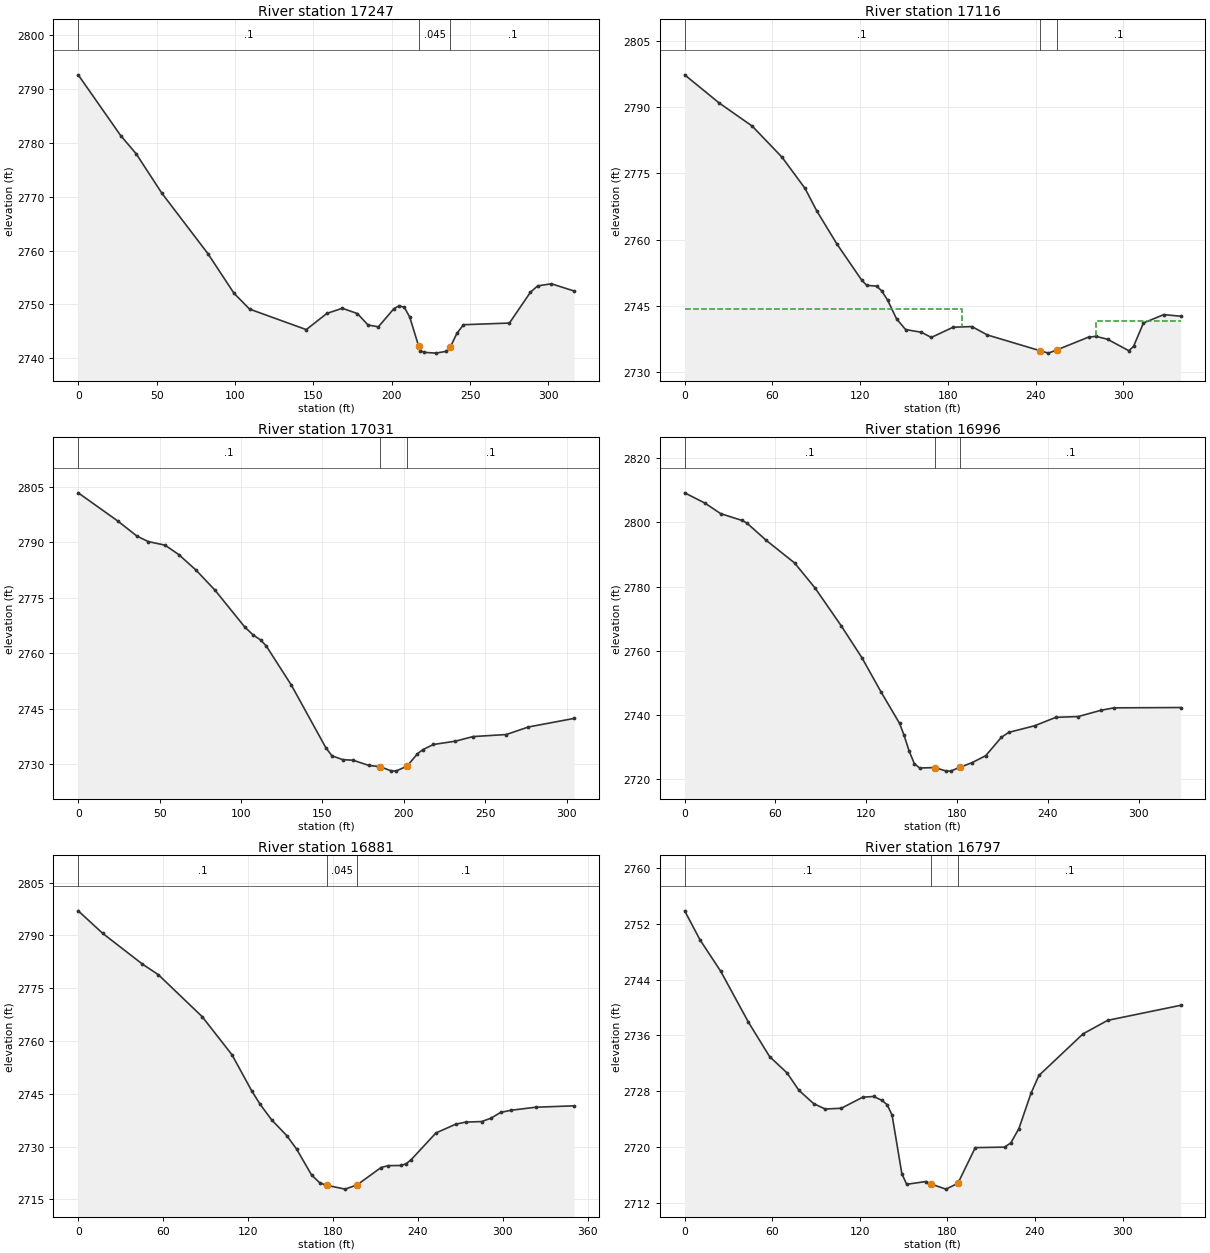
Type RM Length L Ch R = 1 ,17247   ,130.9,130.9,130.9
XS GIS Cut Line= 3
2114104.49884263379662.1658953732114116.99881762379466.332625613
 2114093.0405322379348.624199614
#Sta/Elev= 30
       0  2792.6    27.1 2781.33      37 2777.95    53.4 2770.63    82.8 2759.41
    99.4 2752.08   109.3 2749.15   145.5 2745.34   158.6 2748.34   168.5  2749.3
   178.1 2748.32   184.9  2746.2   191.5 2745.86   201.4 2749.23   204.8 2749.77
   208.1 2749.46   211.5 2747.67   217.2 2742.28   218.2 2741.46   220.8 2741.13
   228.2 2740.98   234.9 2741.32   237.5 2742.18   241.6 2744.65   245.8 2746.25
   275.1 2746.56   288.5 2752.27   293.1 2753.45   301.9 2753.84   316.4  2752.5
#Mann= 3 ,-1 , 0
       0      .1       0   217.2    .045       0   237.5      .1       0
Bank Sta=217.2,237.5
XS Rating Curve= 0 ,0
Exp/Cntr=0.3,0.1

Type RM Length L Ch R = 1 ,17116   ,84.7,84.7,84.7
XS GIS Cut Line= 4
2114161.12290839  379666.51375362114211.23781745 379485.29014306
2114261.35272651379368.3553552542114266.92104974379345.069639934
#Sta/Elev= 30
       0 2797.28    23.6 2790.91    46.2 2785.68    66.6 2778.64    82.3  2771.6
    90.4 2766.47   104.1 2759.03   121.1 2750.83   124.5 2749.67   131.3 2749.48
   134.7 2748.44   138.8 2746.32   144.9 2742.09   151.1 2739.66   161.9 2739.05
   168.7 2737.88   183.6 2740.19   196.4 2740.34   207.1 2738.43   242.8  2734.9
   248.8 2734.33   254.7 2735.08   276.3 2737.96   281.3 2738.12   289.2 2737.47
   303.8 2734.87     307 2735.85   313.8 2741.16   327.7 2743.04   339.2 2742.68
#Mann= 3 ,-1 , 0
       0      .1       0   242.8    .045       0   254.7      .1       0
#XS Ineff= 2 , 0
          189.62 2744.25  281.09         2741.59
Permanent Ineff=
       F       F
Bank Sta=242.8,254.7
XS Rating Curve= 0 ,0
Exp/Cntr(USF)=0,0
Exp/Cntr=0.3,0.1

Type RM Length L Ch R = 1 ,17031   ,34.8,34.8,34.8
XS GIS Cut Line= 4
  2114355.001799379643.2280382792114312.48005798379512.119336799
2114312.98626918379422.0137427322114277.04527379379354.181441581
#Sta/Elev= 30
       0 2803.38    24.2  2795.8    36.1 2791.69      43 2790.21    53.4 2789.23
    61.9 2786.65    72.5 2782.45    84.1 2777.04   102.3 2767.13   107.5 2764.96
     112 2763.64   115.5 2762.02     131 2751.38   152.2 2734.45   155.9 2732.31
   162.5 2731.28     169 2731.11   178.6  2729.7   185.4 2729.39     192 2728.29
   195.1 2728.17     202  2729.5   208.4 2732.85   211.6 2733.94   218.2 2735.37
   231.8 2736.27   242.6 2737.51     263 2738.06   276.6  2740.1   304.7 2742.42
#Mann= 3 ,-1 , 0
       0      .1       0   185.4    .045       0     202      .1       0
Bank Sta=185.4,202
XS Rating Curve= 0 ,0
Exp/Cntr(USF)=0,0
Exp/Cntr=0.3,0.1

Type RM Length L Ch R = 1 ,16996   ,128.62,115.28,101.94
XS GIS Cut Line= 3
2114401.37390503379621.5409766142114321.16573212 379382.99913086
2114262.83218738379334.040895447
#Sta/Elev= 30
       0 2809.17    13.4 2805.97    23.8 2802.69    37.6 2800.62    41.1 2799.78
    53.9 2794.38    72.6 2787.36    86.1 2779.59   103.4 2767.82   117.2 2757.79
   129.9 2747.09     142 2737.42   144.9 2733.85   148.4 2728.74   151.8 2724.86
   155.3  2723.5   165.3 2723.64   172.6 2722.59   175.7 2722.53   182.1 2723.76
   189.9 2725.15     199 2727.35   209.3 2733.05   214.1 2734.57   231.4 2736.67
   245.3 2739.27   260.2 2739.53   275.2 2741.48   283.8 2742.23   327.8 2742.33
#Mann= 3 ,-1 , 0
       0      .1       0   165.3    .045       0   182.1      .1       0
Bank Sta=165.3,182.1
XS Rating Curve= 0 ,0
Exp/Cntr=0.3,0.1

Type RM Length L Ch R = 1 ,16881   ,86.59,84.15,81.71
XS GIS Cut Line= 2
2114601.37383312379452.7909860312114274.29049778379326.749243364
#Sta/Elev= 30
       0 2796.96    17.3 2790.56    45.4 2781.82    56.7  2778.8    87.6  2766.9
   108.7 2756.05   122.7 2745.76   128.6 2741.97   136.8 2737.53   147.4 2733.09
   154.4 2729.24   164.9 2721.92   170.9 2719.61     176 2718.94   188.7 2717.89
   197.3 2719.14     214 2724.03   219.1 2724.56   228.2 2724.61   231.8 2725.12
   235.3 2726.25   252.8 2733.84   266.9 2736.36   273.9 2736.93   285.1 2737.09
   291.5 2738.01   298.5 2739.67   305.6 2740.28   323.2 2741.16   350.5 2741.56
#Mann= 3 ,-1 , 0
       0      .1       0     176    .045       0   197.3      .1       0
Bank Sta=176,197.3
XS Rating Curve= 0 ,0
Exp/Cntr=0.3,0.1

Type RM Length L Ch R = 1 ,16797   ,116.95,124.98,133
XS GIS Cut Line= 2
2114615.95713729379341.3325475312114283.66547903379270.499355868
#Sta/Elev= 30
       0 2753.83    10.5 2749.68    24.7 2745.18    43.7 2737.89    58.2 2732.97
    70.1 2730.65    78.3 2728.14    88.4 2726.24    96.3 2725.47   107.3 2725.58
     122 2727.16   129.4 2727.27     135 2726.73   138.7  2726.1   142.1  2724.6
   148.8 2716.22   152.1  2714.7   165.4  2715.1   168.9 2714.73     179 2714.01
   187.2 2714.84   199.1 2719.95   219.2 2720.02   223.5 2720.63     229 2722.68
   237.3 2727.73   242.7 2730.27   272.9 2736.22   289.8 2738.16   339.8 2740.31
#Mann= 3 ,-1 , 0
       0      .1       0   168.9    .045       0   187.2      .1       0
Bank Sta=168.9,187.2
XS Rating Curve= 0 ,0
Exp/Cntr=0.3,0.1

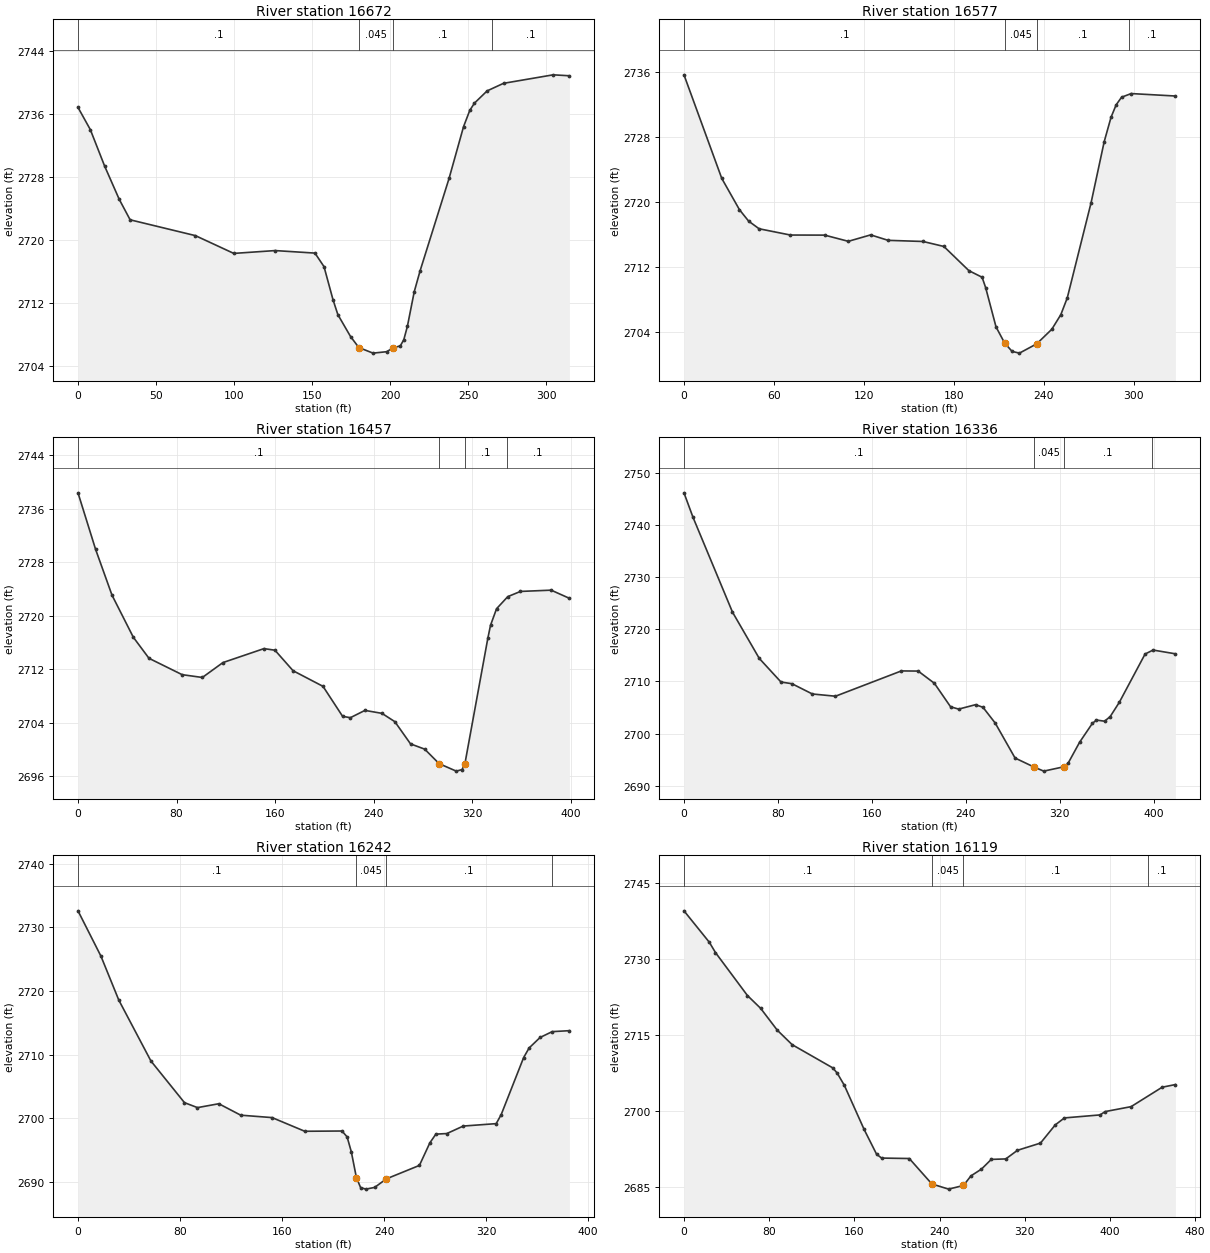
Type RM Length L Ch R = 1 ,16672   ,93.18,94.81,96.45
XS GIS Cut Line= 2
 2114609.7071498379310.0826100262114377.41561961379097.582706943
#Sta/Elev= 30
       0 2736.84     7.9 2734.02    17.1 2729.37    26.4 2725.17    33.4 2722.56
    75.2 2720.55    99.8 2718.29   126.3 2718.65   151.8 2718.33   157.6 2716.61
   163.4 2712.38   166.5  2710.5   174.6 2707.73   179.9 2706.33     189 2705.62
   197.7  2705.8   201.7 2706.26   206.5 2706.55   208.7 2707.31     211 2709.01
   215.4 2713.42   219.2 2716.11   237.7 2727.81     247  2734.4     251 2736.47
     254 2737.39   262.1 2738.94   272.6  2739.9   304.4 2740.98   314.8 2740.86
#Mann= 4 ,-1 , 0
       0      .1       0   179.9    .045       0   201.7      .1       0
  265.17      .1       0
Bank Sta=179.9,201.7
XS Rating Curve= 0 ,0
Exp/Cntr=0.3,0.1

Type RM Length L Ch R = 1 ,16577   ,120.1,119.78,119.46
XS GIS Cut Line= 2
2114677.41567579 379275.70767878 2114460.7487863379029.874180943
#Sta/Elev= 30
       0 2735.61    25.2  2722.9      37 2719.06    43.1 2717.66    50.1 2716.72
      71 2715.95    93.8 2715.94   109.6 2715.18   124.5 2715.97   136.1  2715.3
   159.4 2715.16   173.3 2714.55     190 2711.58   198.8 2710.77   201.2 2709.48
   208.1 2704.67   213.8 2702.71   218.8 2701.67   223.7 2701.46  235.242702.602
   245.3 2704.39   251.3 2706.18   255.6 2708.24   271.5 2719.93   280.2 2727.39
   284.8 2730.41   288.2 2731.93   291.8 2732.86   298.2 2733.31   327.7 2733.01
#Mann= 4 ,-1 , 0
       0      .1       0   213.8    .045       0  235.24      .1       0
  296.66      .1       0
Bank Sta=213.8,235.24
XS Rating Curve= 0 ,0
Exp/Cntr=0.3,0.1

Type RM Length L Ch R = 1 ,16457   ,114.65,121.19,127.73
XS GIS Cut Line= 3
2114708.66561329379265.2910329552114680.54066953379107.999352783
2114519.08233103378931.957710117
#Sta/Elev= 30
       0 2738.41    14.3 2729.94    27.6 2723.09    44.9 2716.79    57.6 2713.64
    84.5 2711.19   100.9 2710.77   117.6    2713   150.9 2715.09   159.8 2714.85
   174.5 2711.78   198.8 2709.44   214.7 2704.95     221 2704.75   232.8 2705.84
   246.6  2705.4   257.1 2704.15   269.8 2700.83   281.3 2700.04     293 2697.87
   306.9 2696.75   311.6 2696.98   313.9 2697.84   332.5 2716.62   334.7 2718.58
   339.6 2721.06   348.7 2722.87     359 2723.65   383.9 2723.84   398.7 2722.62
#Mann= 4 ,-1 , 0
       0      .1       0     293    .045       0   313.9      .1       0
  347.82      .1       0
Bank Sta=293,313.9
XS Rating Curve= 0 ,0
Exp/Cntr=0.3,0.1

Type RM Length L Ch R = 1 ,16336   ,96.01,93.87,91.73
XS GIS Cut Line= 3
2114780.54046956 379229.874109032114716.99892995379045.499149695
2114648.24906746378832.999246612
#Sta/Elev= 30
       0 2746.15     7.7 2741.45    41.3 2723.28    64.1 2714.41    82.6 2709.88
    91.9 2709.56   109.3 2707.59     129 2707.16   185.1 2712.01   199.4 2711.98
   213.2 2709.64     227 2705.13   233.9 2704.69   248.3 2705.54   254.6 2705.03
     265 2702.01   281.9 2695.31   297.6 2693.63   306.3  2692.8  323.362693.628
     327 2694.29   336.8 2698.32   347.7 2701.95   351.2 2702.59   358.1 2702.37
   362.9 2703.26   370.7 2706.01   392.6 2715.25   399.4 2716.01   418.4 2715.29
#Mann= 4 ,-1 , 0
       0      .1       0   297.6    .045       0  323.36      .1       0
  398.13      .1       0
Bank Sta=297.6,323.36
XS Rating Curve= 0 ,0
Exp/Cntr=0.3,0.1

Type RM Length L Ch R = 1 ,16242   ,126.61,123.18,119.75
XS GIS Cut Line= 3
2114875.33227471379131.9576382042114763.87383622378904.874102861
2114678.25026162378803.960604231
#Sta/Elev= 30
       0 2732.62      18 2725.49      32 2718.58    57.2    2709    83.5 2702.45
    93.7 2701.67   110.4 2702.28   127.6 2700.48   152.2  2700.1   177.8 2697.95
     207 2697.99     211 2697.07   214.3 2694.73   218.3 2690.66   221.6 2689.09
   225.7 2688.85   232.6 2689.12  241.762690.461   267.7 2692.58   275.9 2696.13
   280.6  2697.5   289.2 2697.59   302.1 2698.77   327.9 2699.15   331.8 2700.56
   349.4 2709.53   353.7 2711.05   362.3  2712.7   371.8 2713.62   385.3 2713.77
#Mann= 4 ,-1 , 0
       0      .1       0   218.3    .045       0  241.76      .1       0
  371.61      .1       0
Bank Sta=218.3,241.76
XS Rating Curve= 0 ,0
Exp/Cntr=0.3,0.1

Type RM Length L Ch R = 1 ,16119   ,145.06,143.65,142.2
XS GIS Cut Line= 3
2115039.91560695379064.2491122042114837.83234972378816.332613289
 2114726.3739112378728.832460195
#Sta/Elev= 30
       0 2739.43    23.8 2733.24    29.6  2731.2    59.6 2722.74      72 2720.22
    87.6 2715.92   101.6 2713.06   139.7 2708.49   143.9 2707.46   150.6 2705.05
   169.2 2696.35   180.9 2691.47   185.6 2690.72   211.6 2690.63   232.8 2685.62
   248.5  2684.6   262.5 2685.32   269.5 2687.21   279.4 2688.55   288.6 2690.46
   302.2 2690.55   313.2 2692.25   334.8 2693.67   348.7 2697.26   357.3 2698.63
   390.7 2699.22   395.6 2699.88   419.9 2700.85   449.1 2704.68   461.5  2705.2
#Mann= 4 ,-1 , 0
       0      .1       0   232.8    .045       0   262.5      .1       0
  435.38      .1       0
Bank Sta=232.8,262.5
XS Rating Curve= 0 ,0
Exp/Cntr=0.3,0.1

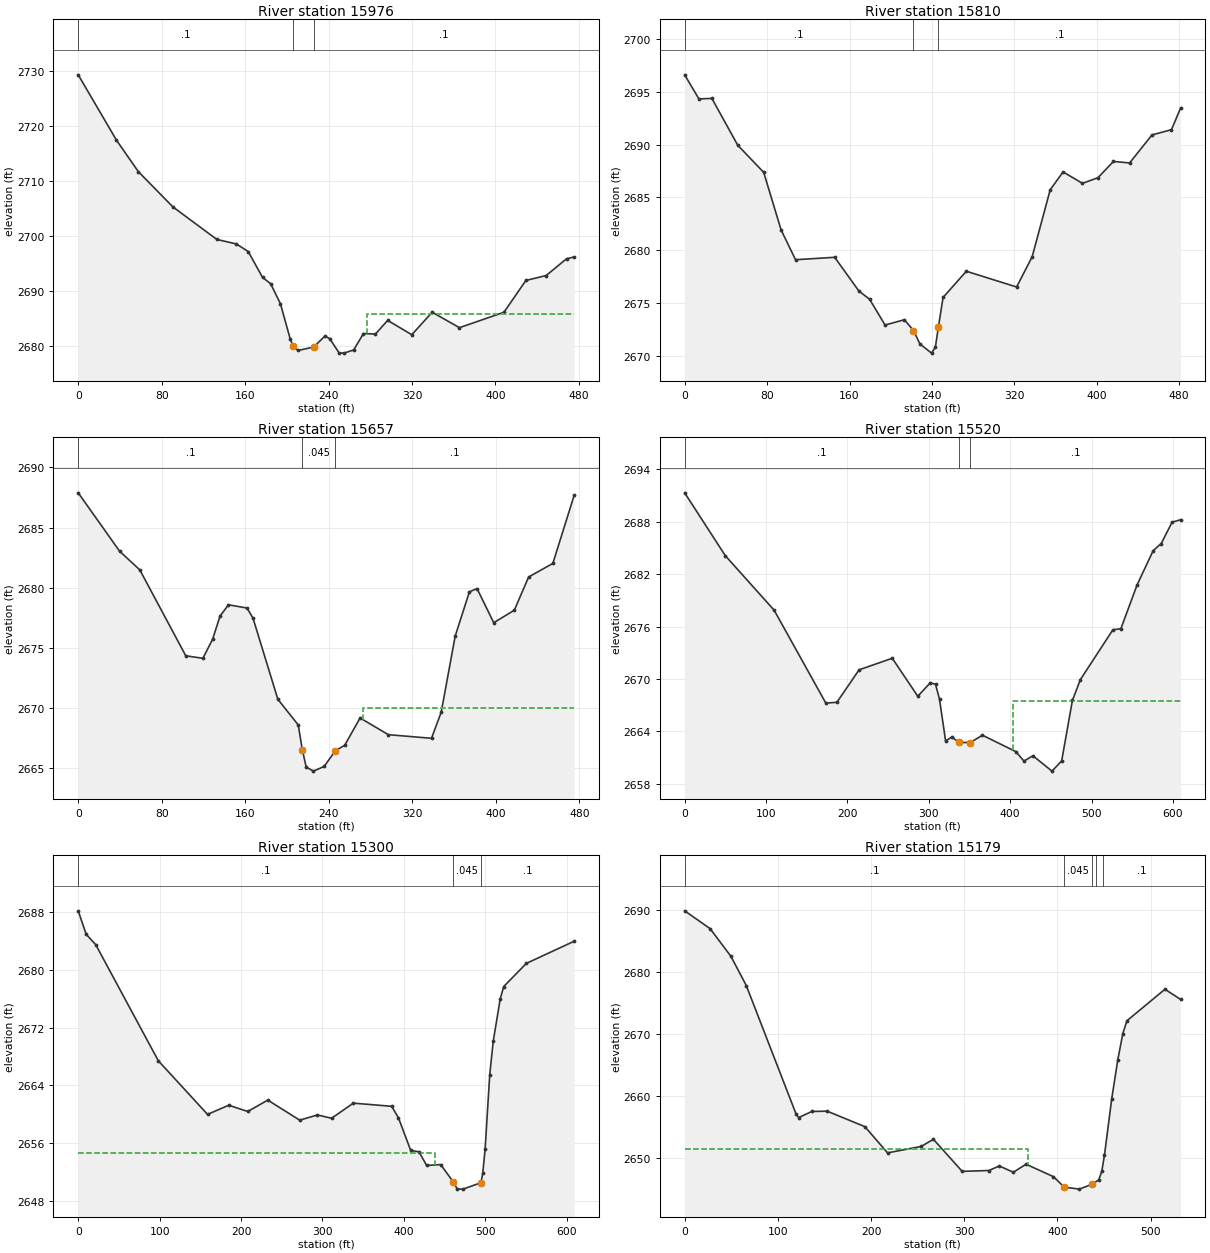
Type RM Length L Ch R = 1 ,15976   ,169.76,165.26,160.79
XS GIS Cut Line= 3
2115163.87402046378967.3743059492114958.66544136378757.999396622
2114805.54074761378659.040933117
#Sta/Elev= 30
       0 2729.32    36.7 2717.43    57.6 2711.73    90.7 2705.32   132.9 2699.39
   151.7 2698.57     163 2697.19   176.7  2692.5   184.5 2691.34   193.9  2687.7
   203.2 2681.33   206.1    2680   210.7  2679.2  225.722679.826   236.5 2681.81
   241.1 2681.36   250.1 2678.77   254.8 2678.72   264.1  2679.3   273.5 2682.28
     285 2682.19   296.7 2684.67   319.8 2682.07   339.4 2686.16   365.5 2683.35
   408.2 2686.15   429.2 2691.93   448.7 2692.83   468.2 2695.88   475.5  2696.2
#Mann= 3 ,-1 , 0
       0      .1       0   206.1    .045       0  225.72      .1       0
#XS Ineff= 2 , 0
                          276.74         2685.83
Permanent Ineff=
       F       F
Bank Sta=206.1,225.72
XS Rating Curve= 0 ,0
Exp/Cntr=0.3,0.1

Type RM Length L Ch R = 1 ,15810   ,154.61,153.64,152.67
XS GIS Cut Line= 3
2115201.37394544378825.7075945292115111.79046321378713.207491443
2114816.99905804378548.624159202
#Sta/Elev= 30
       0 2696.61    13.8 2694.33    26.4 2694.38    51.5 2689.95    76.7 2687.38
    93.6 2681.93   107.6 2679.11   145.6 2679.34   169.1 2676.15   179.5 2675.37
   194.5 2672.93   213.3 2673.43   222.1 2672.41   228.3 2671.15   239.6 2670.27
   243.3 2670.81   246.3 2672.74   250.8 2675.54   273.4 2678.02   322.2 2676.53
   337.3 2679.39   354.8 2685.73   367.3 2687.42   386.1 2686.34   401.1 2686.87
   416.2 2688.41   431.9 2688.27   453.6 2690.92   472.5 2691.42   481.4 2693.47
#Mann= 3 ,-1 , 0
       0      .1       0   222.1    .045       0   246.3      .1       0
Bank Sta=222.1,246.3
XS Rating Curve= 0 ,0
Exp/Cntr=0.3,0.1

Type RM Length L Ch R = 1 ,15657   ,169.24,168.86,168.49
XS GIS Cut Line= 3
2115330.54068187 378686.124212282115203.45727462378591.332407117
2114918.04052264378454.874346703
#Sta/Elev= 30
       0 2687.89    39.6 2683.04      59 2681.48     103 2674.34   119.4 2674.13
   128.7 2675.72   135.8 2677.64   143.9 2678.58   161.7 2678.31   167.4 2677.46
   191.2 2670.72   210.7 2668.59   214.6 2666.52   218.3 2665.09   225.2 2664.75
   235.5 2665.14  246.332666.453   255.2  2666.9   269.9 2669.17     297 2667.78
   338.3 2667.48   347.6 2669.65     361 2675.98   374.6 2679.66   381.9 2679.93
   397.9 2677.09   417.6 2678.13   431.3 2680.89   454.5 2682.02   474.9 2687.68
#Mann= 3 ,-1 , 0
       0      .1       0   214.6    .045       0  246.33      .1       0
#XS Ineff= 2 , 0
                          272.67         2670.03
Permanent Ineff=
       F       F
Bank Sta=214.6,246.33
XS Rating Curve= 0 ,0
Exp/Cntr=0.3,0.1

Type RM Length L Ch R = 1 ,15520   ,183.52,187.72,191.93
XS GIS Cut Line= 4
2115452.25864108378661.5027098992115244.97017078378463.783273498
2115166.44724654378419.1628261222114935.71344795378388.934000817
#Sta/Elev= 30
       0  2691.3    49.9 2684.11     110 2677.86   173.5 2667.23   187.1 2667.33
   214.3 2671.04   255.1 2672.37   286.5 2668.02   301.9 2669.57   308.3 2669.39
   313.2 2667.67   320.7 2662.89   328.3 2663.36   337.1 2662.73   350.9 2662.72
     366 2663.56     407 2661.68     417  2660.6     428 2661.21   451.4 2659.45
   463.3 2660.62   476.5 2667.54   486.3 2669.92   526.2 2675.62   536.1 2675.75
   555.9 2680.74   575.8 2684.69   585.7  2685.5     599 2687.94   609.5 2688.22
#Mann= 3 ,-1 , 0
       0      .1       0   337.1    .045       0   350.9      .1       0
#XS Ineff= 2 , 0
                          403.46         2667.45
Permanent Ineff=
       F       F
Bank Sta=337.1,350.9
XS Rating Curve= 0 ,0
Exp/Cntr=0.3,0.1

Type RM Length L Ch R = 1 ,15300   ,119.58,121.35,123.11
XS GIS Cut Line= 3
2115512.83231205378570.4991154522115271.16547254378293.416008204
2115086.79051322378137.165992618
#Sta/Elev= 30
       0 2688.19     9.8 2684.93    21.5  2683.5    98.4 2667.39   158.9 2659.95
     185 2661.22   208.3 2660.35   232.9 2661.93   272.1 2659.15   293.9 2659.87
   311.3 2659.41     338 2661.51   385.1 2661.07   393.3 2659.51   408.5 2654.95
   418.7 2654.76   428.1 2652.86   445.3 2652.99     461 2650.55   465.7 2649.59
   472.7 2649.58   494.8 2650.47     497 2651.76   499.9  2655.1   505.6 2665.47
   509.9  2670.1   518.5 2675.99   522.8 2677.69   550.6  2680.9   609.3 2683.97
#Mann= 3 ,-1 , 0
       0      .1       0     461    .045       0   494.8      .1       0
#XS Ineff= 2 , 0
          438.54 2654.57
Permanent Ineff=
       F       F
Bank Sta=461,494.8
XS Rating Curve= 0 ,0
Exp/Cntr=0.3,0.1

Type RM Length L Ch R = 1 ,15179   ,271.16,272.48,273.8
XS GIS Cut Line= 3
2115557.62388912378489.249277949 2115404.4988673378277.791039452
2115218.04057878378080.915777028
#Sta/Elev= 30
       0 2689.79    27.3 2686.92    49.6 2682.47    66.1 2677.76   119.6 2657.04
   122.4  2656.5   136.5 2657.48     153 2657.52   193.4 2655.03   217.7 2650.81
   253.8 2651.84   266.9    2653   297.8 2647.83   326.5 2647.97   337.6  2648.7
   352.7 2647.69   366.3 2648.98   395.7 2646.98  407.25  2645.3   423.5 2644.97
   437.32645.766   444.4 2646.48   447.6 2647.84   450.5 2650.47   458.3 2659.56
   464.8 2665.81   470.2 2670.03   474.6 2672.09   515.4 2677.16   532.2 2675.52
#Mann= 5 ,-1 , 0
       0      .1       0  407.25    .045       0   437.3      .1       0
  440.93      .1       0  448.49      .1       0
#XS Ineff= 2 , 0
          368.08 2651.37
Permanent Ineff=
       F       F
Bank Sta=407.25,437.3
XS Rating Curve= 0 ,0
Exp/Cntr=0.3,0.1