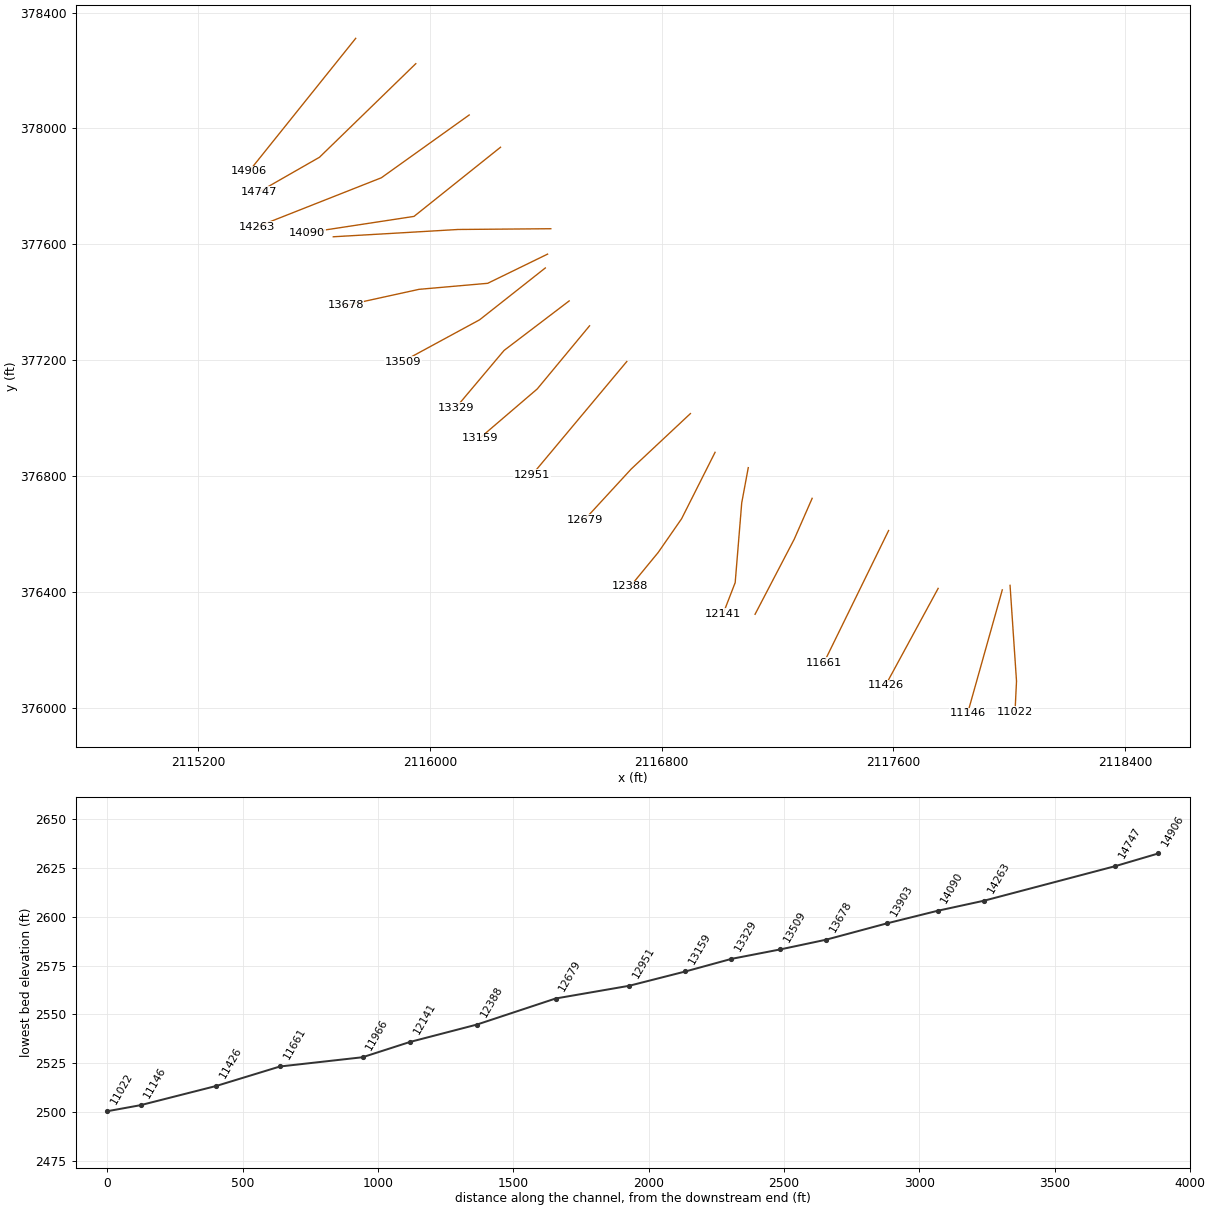
HEC-RAS study ROARINGCK.prj: ROARINGCK

--- ROARINGCK.g01 (geometry) --- (continued)

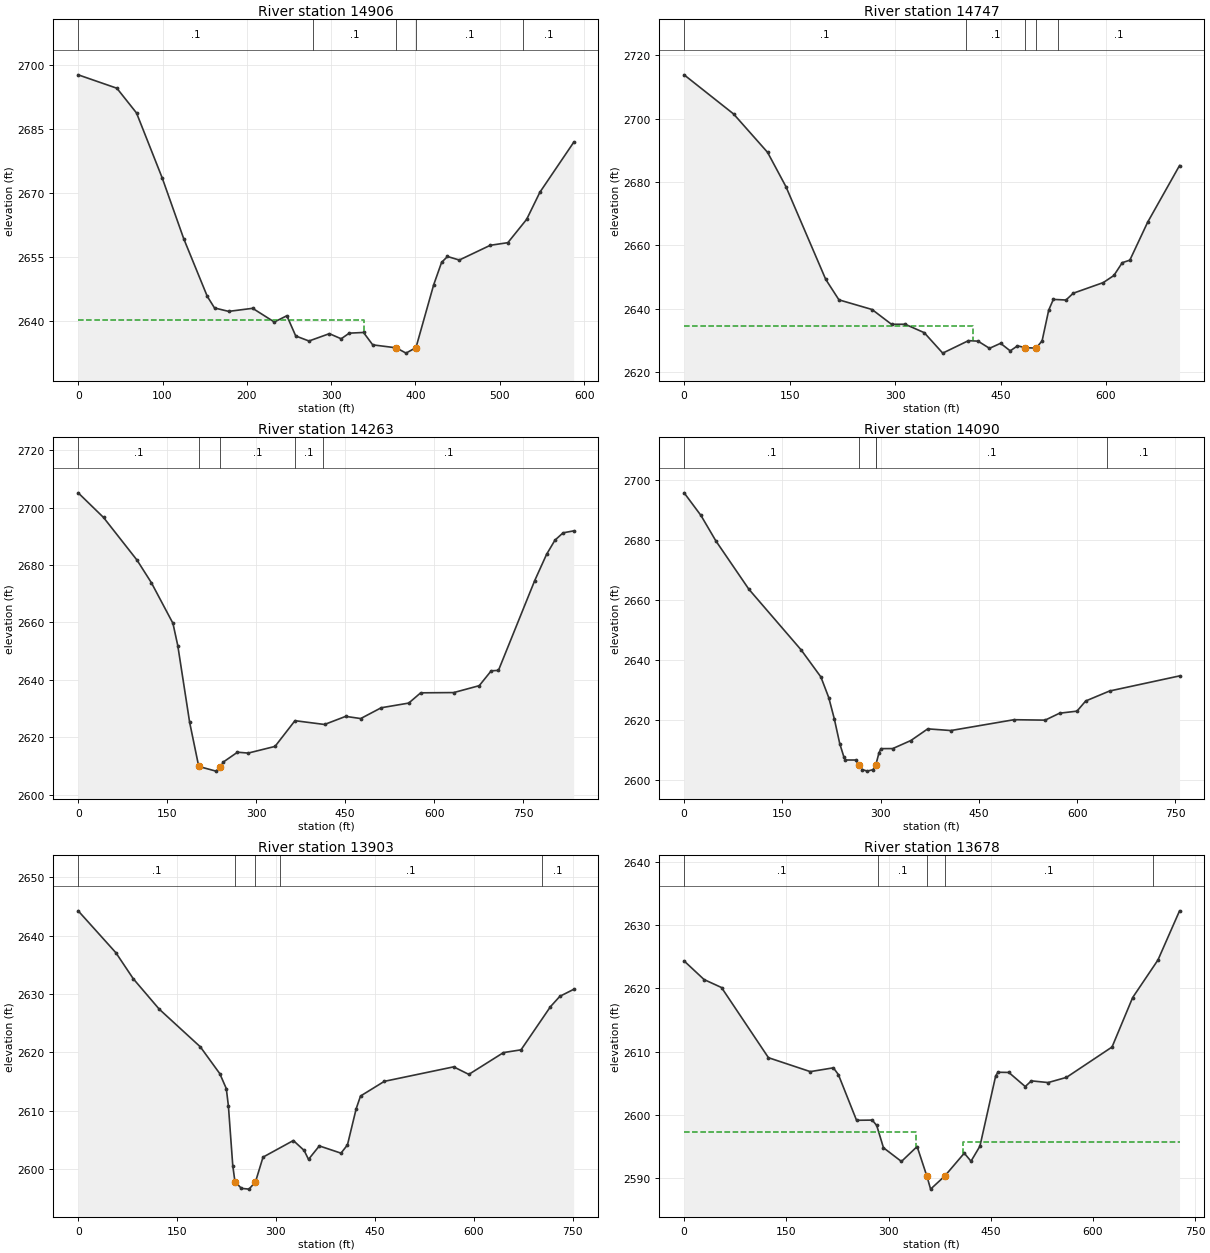
Type RM Length L Ch R = 1 ,14906   ,164.64,158.92,153.21
XS GIS Cut Line= 2
2115744.08217764378311.1243061132115376.37392354377852.790905192
#Sta/Elev= 30
       0  2697.7    45.9 2694.56    69.2 2688.76    99.6 2673.57   125.2 2659.29
   153.1  2645.8   161.7 2643.08   178.5 2642.28   206.9    2643   232.6 2639.79
   247.5 2641.26     258 2636.52   273.7 2635.34   297.9 2637.06   311.9 2635.86
   321.5 2637.18   338.4 2637.34   349.3 2634.44   377.3 2633.74   388.8  2632.5
   400.6 2633.79   421.6  2648.5     431 2653.76     438 2655.14     452 2654.31
   488.7 2657.76   509.6 2658.38   531.9 2663.85   547.6  2670.2   587.6 2681.87
#Mann= 5 ,-1 , 0
       0      .1       0     278      .1       0   377.3    .045       0
   400.6      .1       0  527.91      .1       0
#XS Ineff= 2 , 0
          339.56  2640.2
Permanent Ineff=
       F       F
Bank Sta=377.3,400.6
XS Rating Curve= 0 ,0
Exp/Cntr=0.3,0.1

Type RM Length L Ch R = 1 ,14747   ,483.76,484.4,484.94
XS GIS Cut Line= 3
2115951.37408587378223.6241530332115619.08242762377900.707476035
2115409.70719022377780.916048944
#Sta/Elev= 30
       0 2713.86    70.4  2701.5   118.7 2689.39   144.9 2678.52   201.4 2649.29
   220.2 2642.82   267.3 2639.77     295  2635.1   314.4 2635.12   341.5 2632.46
   367.8    2626   404.4 2629.94     418 2629.78   434.3 2627.52   450.1  2629.1
   463.8 2626.71   474.1  2628.3   485.5 2627.72   500.5 2627.58   509.1 2629.86
   518.5 2639.56   525.1 2642.96   543.1 2642.77   553.4 2644.91   596.1 2648.27
   611.2 2650.51   623.1 2654.55   633.9 2655.35   659.2 2667.32   704.6 2685.23
#Mann= 5 ,-1 , 0
       0      .1       0  400.72      .1       0   485.5    .045       0
   500.5      .1       0  531.16      .1       0
#XS Ineff= 2 , 0
          411.46 2634.57
Permanent Ineff=
       F       F
Bank Sta=485.5,500.5
XS Rating Curve= 0 ,0
Exp/Cntr=0.3,0.1

Type RM Length L Ch R = 1 ,14263   ,171.74,172.41,173.18
XS GIS Cut Line= 3
2116135.74904522378046.540845782 2115832.6239953377829.874284372
2115402.41553813377660.082629204
#Sta/Elev= 30
       0 2705.11    42.7 2696.54    99.2 2681.69   123.4 2673.83   159.7 2659.72
   167.9 2651.93   187.9 2625.22   203.2 2609.92   232.2 2608.29  239.732609.653
   244.3 2611.41   268.5 2614.87   286.6 2614.57   331.8 2616.89   365.4 2625.84
   415.2 2624.52   450.9 2627.34   476.2 2626.58   510.8 2630.34   557.1 2631.96
   577.3 2635.53     633 2635.62     676 2638.02   696.2 2643.19   708.4 2643.34
   769.5 2674.58   789.5 2683.71   803.6 2688.64   817.3 2691.19   835.1 2691.87
#Mann= 5 ,-1 , 0
       0      .1       0   203.2    .045       0  239.73      .1       0
  364.95      .1       0  412.67      .1       0
Bank Sta=203.2,239.73
XS Rating Curve= 0 ,0
Exp/Cntr=0.3,0.1

Type RM Length L Ch R = 1 ,14090   ,198.47,187.65,176.84
XS GIS Cut Line= 3
2116243.90860578377935.2562914492115945.29765445377696.540889621
2115575.50574312377640.117446035
#Sta/Elev= 30
       0 2695.65    25.7 2688.13    48.5 2679.66    98.9 2663.58   178.7  2643.4
   208.8 2634.42   220.8 2627.56   229.2 2620.58   237.6 2612.25   243.8 2607.89
   246.1 2606.79   262.1 2606.79   267.3 2605.04   271.8 2603.63   279.6 2603.09
   288.4 2603.57   292.8 2605.28   297.5 2609.16   300.6 2610.57   318.5 2610.59
   346.2 2613.27     372 2617.15   407.3 2616.59   503.6 2620.19   551.2 2620.05
   573.3 2622.36   599.8 2623.04   613.1 2626.42   649.6 2629.74   756.4 2634.76
#Mann= 5 ,-1 , 0
       0      .1       0   267.3    .045       0   292.8      .1       0
  292.93      .1       0   645.6      .1       0
Bank Sta=267.3,292.8
XS Rating Curve= 0 ,0
Exp/Cntr=0.3,0.1

Type RM Length L Ch R = 1 ,13903   ,223.29,224.51,225.74
XS GIS Cut Line= 4
2116417.51980713 377654.006197782116097.20712754377651.401872277
 2115891.4782083377639.2493375392115666.65155822377626.228366196
#Sta/Elev= 30
       0 2644.22    57.3 2637.04    83.6  2632.6   122.9 2627.41   185.3 2620.96
   214.8 2616.38   224.7 2613.82   227.9 2610.83   234.5 2600.65   237.8 2597.92
   247.6 2596.76   259.1 2596.63   268.9 2597.85   280.4  2602.1   326.4 2604.94
   342.8 2603.24   349.4 2601.72   365.8 2604.02   398.7 2602.78   408.5  2604.2
   421.7 2610.37   428.3 2612.55   464.4 2615.06   569.6 2617.54   592.6 2616.25
   645.2 2619.98   671.8 2620.45   716.4 2627.82   730.8 2629.61   751.6 2630.79
#Mann= 5 ,-1 , 0
       0      .1       0   237.8    .045       0   268.9      .1       0
  306.51      .1       0  703.45      .1       0
Bank Sta=237.8,268.9
XS Rating Curve= 0 ,0
Exp/Cntr=0.3,0.1

Type RM Length L Ch R = 1 ,13678   ,162.66,168.89,175.11
XS GIS Cut Line= 4
2116406.23505279377566.3324886112116199.63769695377465.638136193
2115962.65851212377444.8048445282115709.18657812 377389.24918136
#Sta/Elev= 30
       0 2624.32    29.3 2621.38    54.9 2620.12   123.8 2609.03   185.2 2606.83
   219.1 2607.43   226.4 2606.37   253.1 2599.14   276.1 2599.17   282.7 2598.32
   292.6  2594.8     319 2592.63     342 2594.99   356.4 2590.28   361.8 2588.26
   382.6 2590.33   411.2 2593.94   421.1 2592.67   434.2 2595.05   457.3 2606.15
   460.6 2606.73   476.6  2606.7   500.7 2604.47   509.7 2605.37   534.3  2605.1
   561.2 2605.92   628.1 2610.72   658.4 2618.54   695.5 2624.47   727.2 2632.24
#Mann= 5 ,-1 , 0
       0      .1       0  285.16      .1       0   356.4    .045       0
   382.6      .1       0  688.73      .1       0
#XS Ineff= 2 , 0
          340.92 2597.34  409.73         2595.75
Permanent Ineff=
       F       F
Bank Sta=356.4,382.6
XS Rating Curve= 0 ,0
Exp/Cntr=0.3,0.1

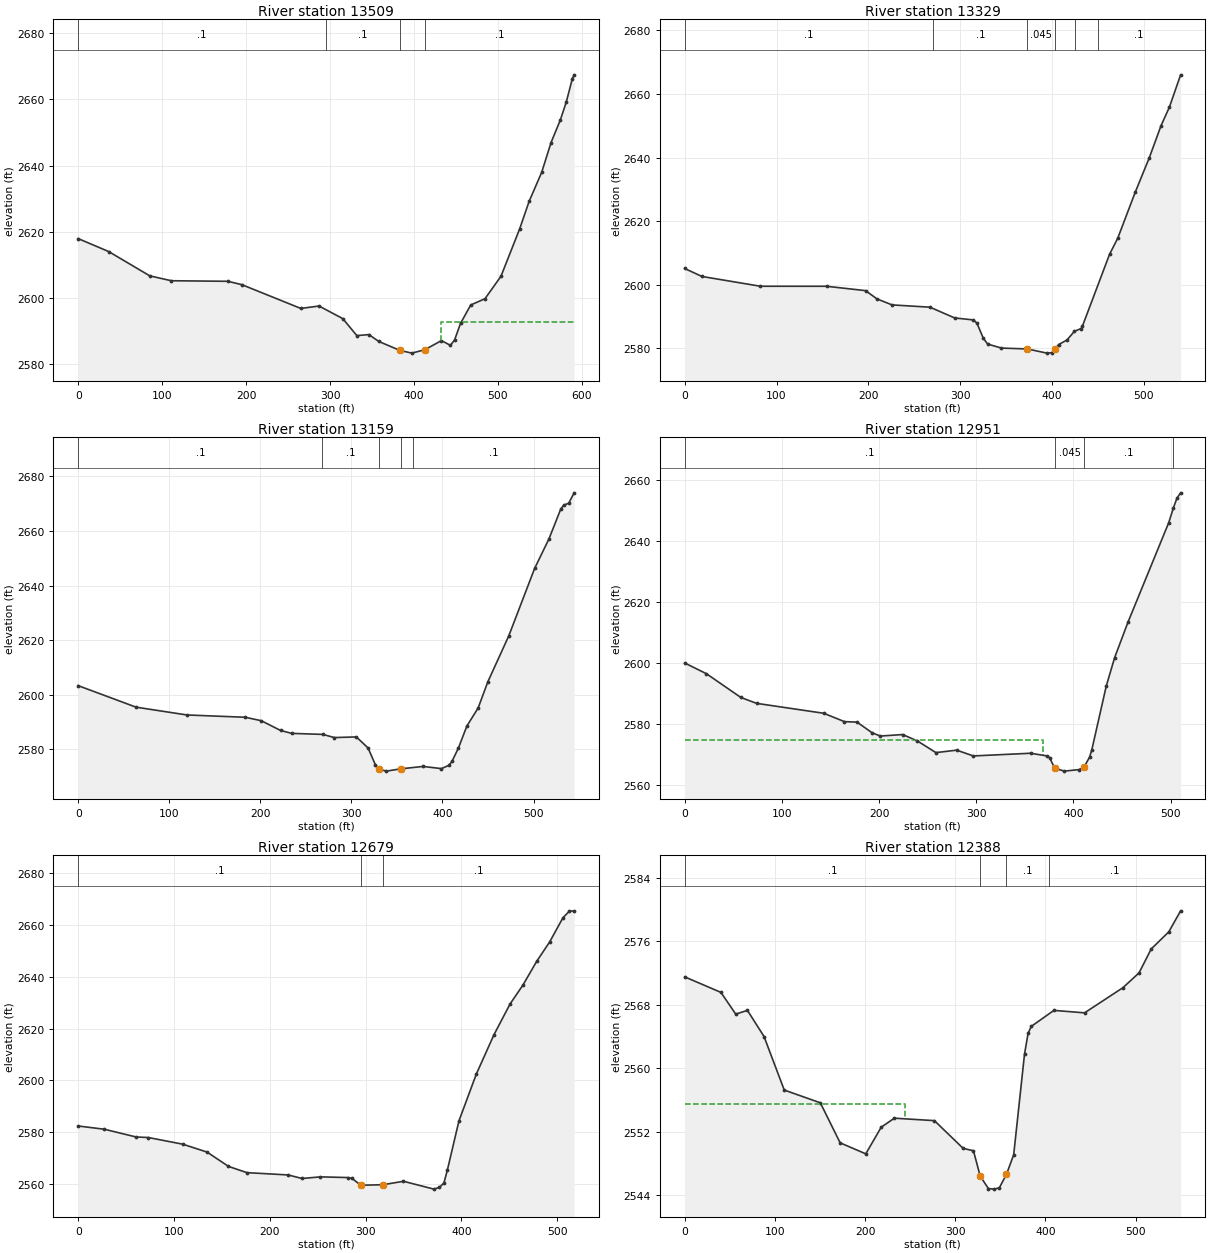
Type RM Length L Ch R = 1 ,13509   ,174.96,180.72,186.48
XS GIS Cut Line= 3
2116398.42240438377518.5894738582116171.86019346377339.769949615
2115906.23506853 377195.67279686
#Sta/Elev= 30
       0 2617.92    36.2 2614.02    85.3 2606.65     111 2605.18   178.3 2605.01
     195 2603.99   265.2  2596.8   286.9 2597.54   315.2 2593.72   331.9 2588.59
   346.3  2588.9     358 2586.83  383.122584.118   397.5 2583.29  413.132584.342
   432.7 2587.08   443.4 2585.64   448.3 2587.24   455.5 2592.31   467.6 2597.85
   484.6 2599.75   503.6 2606.52     526 2620.94   537.2 2629.21   552.1 2637.95
   563.3 2646.97   574.5  2653.9   581.4 2659.21   588.6 2666.23   590.8 2667.45
#Mann= 4 ,-1 , 0
       0      .1       0  294.94      .1       0  383.12    .045       0
  413.13      .1       0
#XS Ineff= 2 , 0
                           432.6         2592.56
Permanent Ineff=
       F       F
Bank Sta=383.12,413.13
XS Rating Curve= 0 ,0
Exp/Cntr=0.3,0.1

Type RM Length L Ch R = 1 ,13329   ,172.57,170.01,167.45
XS GIS Cut Line= 3
2116480.88779062377404.8741501122116256.06146863377233.867274284
 2116090.2629157377036.818783864
#Sta/Elev= 30
       0 2605.07    18.8 2602.56    82.5 2599.48   154.5 2599.47     197  2598.1
   209.3 2595.51   225.8 2593.61   267.1 2592.89     294  2589.5   314.4 2588.88
   318.2 2587.87   325.2 2583.09   329.9 2581.28   344.9 2580.02  373.132579.746
   394.4 2578.43   399.7 2578.57  403.622579.812   407.2 2581.14   416.3 2582.56
   424.4 2585.31   431.6 2586.16     433 2586.85   462.6 2609.52   471.6 2614.65
   490.5 2629.01   505.9 2639.94   518.7 2650.03   527.8 2655.87     540 2666.03
#Mann= 6 ,-1 , 0
       0      .1       0  270.76      .1       0  373.13    .045       0
  403.62      .1       0  424.66      .1       0   449.8      .1       0
Bank Sta=373.13,403.62
XS Rating Curve= 0 ,0
Exp/Cntr=0.3,0.1

Type RM Length L Ch R = 1 ,13159   ,205.54,208.05,210.55
XS GIS Cut Line= 3
2116551.20031405 377318.936657952116370.64490089377101.054875866
2116171.86019346376930.915780455
#Sta/Elev= 30
       0  2603.3    63.5 2595.42   119.4 2592.56   183.3 2591.72     201 2590.46
   222.2 2586.88   234.5 2585.81   268.5 2585.44   281.3 2584.28   305.4 2584.51
   318.3 2580.47   326.4 2574.23     330 2572.75   338.4 2571.98  353.92 2572.81
   378.8  2573.7   398.9  2572.9   407.2 2574.13   410.5 2575.58   417.5 2580.44
   426.8  2588.5   439.2 2595.14   449.8 2604.71   472.8 2621.53   501.2 2646.26
     517 2657.13   529.9 2668.02   533.3 2669.47   538.6 2670.14   544.6 2673.96
#Mann= 5 ,-1 , 0
       0      .1       0  268.08      .1       0     330    .045       0
  353.92      .1       0  367.83      .1       0
Bank Sta=330,353.92
XS Rating Curve= 0 ,0
Exp/Cntr=0.3,0.1

Type RM Length L Ch R = 1 ,12951   ,272.3,271.6,270.91
XS GIS Cut Line= 2
2116679.67249805 377195.672796862116352.41560662376804.179813445
#Sta/Elev= 30
       0 2600.02    22.4  2596.5    57.8 2588.73    74.1  2586.8   143.1 2583.56
   164.4 2580.82   177.3 2580.68   192.9 2577.17   201.4 2576.11   224.3  2576.6
   239.5 2574.49   258.5 2570.69   279.9 2571.49     297  2569.6     356 2570.48
   372.3 2569.63   375.4 2569.05  380.892565.544   390.7 2564.63   406.1 2565.14
   411.12566.025   416.7 2569.26   418.9 2571.57   433.8 2592.48   442.4 2601.76
   456.1 2613.33   498.1 2645.95   502.7 2650.59   506.5 2653.93   510.3 2655.69
#Mann= 4 ,-1 , 0
       0      .1       0  380.89    .045       0   411.1      .1       0
   502.7      .1       0
#XS Ineff= 2 , 0
          368.76  2574.7
Permanent Ineff=
       F       F
Bank Sta=380.89,411.1
XS Rating Curve= 0 ,0
Exp/Cntr=0.3,0.1

Type RM Length L Ch R = 1 ,12679   ,288.69,290.97,293.26
XS GIS Cut Line= 3
2116899.29049712  377015.98549222116695.29746678376825.013105109
2116533.83912829376649.666014865
#Sta/Elev= 30
       0 2582.45    27.3  2581.2    60.4 2578.22    73.3    2578   109.1 2575.44
   134.6 2572.38   156.9 2566.87   176.1 2564.47   219.3 2563.57   233.7 2562.21
   252.9 2562.84   281.6 2562.57     286 2562.23     295 2559.61  318.092559.804
   339.6 2561.13   371.4 2558.11     377 2558.76   381.8 2560.44   385.4 2565.41
   397.5  2584.4   415.7 2602.51   434.1 2617.65     451 2629.57   464.2 2636.71
   478.7 2645.94   492.2  2653.4   506.1 2662.74   512.6 2665.21   517.8 2665.41
#Mann= 3 ,-1 , 0
       0      .1       0     295    .045       0  318.09      .1       0
Bank Sta=295,318.09
XS Rating Curve= 0 ,0
Exp/Cntr=0.3,0.1

Type RM Length L Ch R = 1 ,12388   ,239.18,247.14,255.1
XS GIS Cut Line= 4
2116984.36020887376882.3046572062116868.90866813376653.138120785
2116788.17949888376536.8187996152116691.82536086 376419.63104187
#Sta/Elev= 30
       0 2571.52    40.2 2569.56    56.6 2566.82    69.6 2567.29      88 2563.99
   110.4 2557.24   150.4 2555.63   172.4 2550.58   200.8 2549.19   217.9 2552.55
   232.5 2553.69   276.9 2553.38   308.8 2549.88   320.2 2549.58   327.7 2546.37
   336.8 2544.81   343.2 2544.74   348.9 2544.91   356.8 2546.61   364.8 2549.07
   376.8 2561.76   380.8 2564.41   384.3 2565.27   409.4 2567.29   443.4 2566.98
   485.9 2570.15   503.8 2572.02   517.3 2575.04   536.8  2577.2   549.9 2579.85
#Mann= 4 ,-1 , 0
       0      .1       0   327.7    .045       0   356.8      .1       0
  403.98      .1       0
#XS Ineff= 2 , 0
           243.8 2555.48
Permanent Ineff=
       F       F
Bank Sta=327.7,356.8
XS Rating Curve= 0 ,0
Exp/Cntr=0.3,0.1

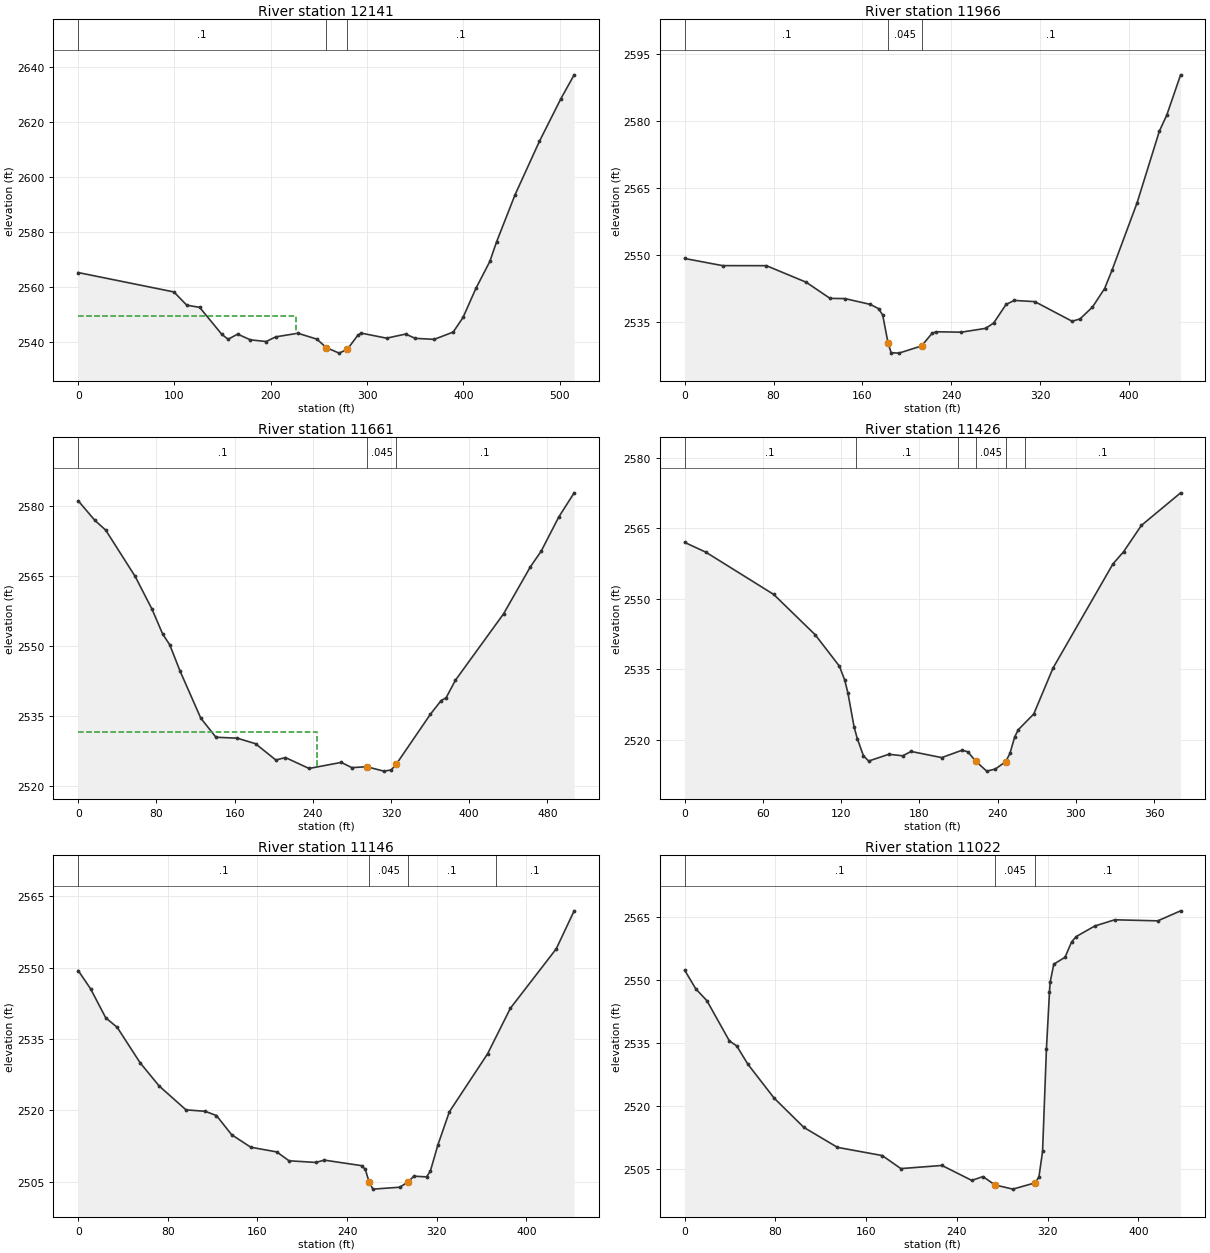
Type RM Length L Ch R = 1 ,12141   ,181.38,175.37,169.36
XS GIS Cut Line= 4
2117098.94331303376829.3533195262117076.37380439376707.825675443
2117053.80462378376432.6520131982117012.13771239 376325.01312086
#Sta/Elev= 30
       0 2565.12    99.4 2558.07   112.8 2553.25   126.1 2552.48   149.2 2542.64
   155.7 2540.88   165.6 2542.74   178.8 2540.66   195.2 2540.05   205.1 2541.74
   228.2 2543.06   247.9 2540.91   257.6 2537.86     271 2535.83   279.5 2537.21
   290.7 2542.47   294.1 2543.09   320.3 2541.27   340.1 2542.76     350 2541.21
   369.7 2540.83   389.5 2543.49   399.7 2548.82   413.1  2559.4   427.5 2569.14
   434.5 2576.26   453.7 2593.39   479.1 2612.89   501.3 2628.31   515.1    2637
#Mann= 3 ,-1 , 0
       0      .1       0   257.6    .045       0   279.5      .1       0
#XS Ineff= 2 , 0
          225.81 2549.25
Permanent Ineff=
       F       F
Bank Sta=257.6,279.5
XS Rating Curve= 0 ,0
Exp/Cntr=0.3,0.1

Type RM Length L Ch R = 1 ,11966   ,304.69,305,305.32
XS GIS Cut Line= 3
2117319.42942062376723.4506441952117257.79765412376582.825597361
2117122.38093022376323.276903868
#Sta/Elev= 30
       0 2549.18    34.1 2547.58    73.5 2547.57   109.3 2543.87   130.8 2540.25
   144.2  2540.2   167.1  2538.9   174.5 2537.94   178.2 2536.52  182.982530.291
   185.8 2528.09   192.8 2527.99  213.19  2529.6   222.6 2532.42   226.3 2532.77
     249 2532.68   270.9 2533.54   278.1 2534.74   289.2 2538.89   296.6 2539.79
   315.1 2539.52   348.7 2535.12   355.8 2535.66   366.9 2538.28   377.9 2542.45
   384.7 2546.64   407.1 2561.63   427.2 2577.71   433.8 2581.26   446.3  2590.3
#Mann= 3 ,-1 , 0
       0      .1       0  182.98    .045       0  213.19      .1       0
Bank Sta=182.98,213.19
XS Rating Curve= 0 ,0
Exp/Cntr=0.3,0.1

Type RM Length L Ch R = 1 ,11661   ,235.47,234.82,234.17
XS GIS Cut Line= 2
2117583.31832853376612.3396459522117360.22822353376156.610242441
#Sta/Elev= 30
       0 2581.18      17 2576.98    28.1  2574.9    58.3 2564.96    75.5 2557.95
    86.4 2552.64    93.7  2550.3   104.1 2544.74   125.4  2534.6   140.9 2530.51
   162.7 2530.31   181.4 2529.13   202.2 2525.63     212 2526.16   236.2 2523.82
   269.1 2525.12     280    2524  295.242524.192   312.6 2523.25   320.2  2523.5
  325.25 2524.69   360.4 2535.46   371.3 2538.37   376.4 2538.97   385.9 2542.72
   435.2 2556.96   462.7 2567.06   473.6 2570.36   491.6 2577.68   507.4 2582.88
#Mann= 3 ,-1 , 0
       0      .1       0  295.24    .045       0  325.25      .1       0
#XS Ineff= 2 , 0
          244.48  2531.7
Permanent Ineff=
       F       F
Bank Sta=295.24,325.25
XS Rating Curve= 0 ,0
Exp/Cntr=0.3,0.1

Type RM Length L Ch R = 1 ,11426   ,276.79,280.21,283.64
XS GIS Cut Line= 2
2117754.32520437376412.686830029 2117572.9016827376078.485398695
#Sta/Elev= 30
       0 2561.97    16.3 2559.88    68.3 2550.89   100.1 2542.31   118.7 2535.61
   122.8  2532.6   125.2 2529.88   129.9  2522.7   132.4 2520.19   137.1 2516.54
   141.1 2515.44   156.6 2516.88   167.2 2516.55   173.6 2517.48   197.1 2516.17
   212.7 2517.74   217.1 2517.41   223.2  2515.4   231.6 2513.29   238.2 2513.73
   246.2 2515.32   249.4 2517.05   253.1 2520.59   255.8  2522.1   267.7 2525.46
   282.4  2535.2   328.4 2557.39   336.5 2559.96   350.2 2565.58   380.3 2572.52
#Mann= 6 ,-1 , 0
       0      .1       0  131.06      .1       0   209.5      .1       0
   223.2    .045       0   246.2      .1       0   261.3      .1       0
Bank Sta=223.2,246.2
XS Rating Curve= 0 ,0
Exp/Cntr=0.3,0.1

Type RM Length L Ch R = 1 ,11146   ,123.2,123.2,123.2
XS GIS Cut Line= 2
2117975.67942047376407.478507116 2117855.8876653375981.263152197
#Sta/Elev= 30
       0  2549.4      11 2545.58    24.6 2539.45    34.8 2537.46    55.3 2529.99
    72.3 2525.11    96.2  2520.1   113.4 2519.79   123.4  2518.9     137 2514.86
   154.1 2512.23   177.2 2511.25   188.2 2509.38     212 2509.04   219.8 2509.52
   252.9 2508.36   256.3 2507.57   259.7 2504.88   263.1 2503.42     287 2503.82
   294.3  2504.9   299.6 2506.14   310.9    2506   314.3 2507.19   321.1 2512.73
   331.3 2519.69   365.4 2531.88   385.8 2541.48   426.7 2553.97   442.7 2561.97
#Mann= 4 ,-1 , 0
       0      .1       0   259.7    .045       0   294.3      .1       0
  372.53      .1       0
Bank Sta=259.7,294.3
XS Rating Curve= 0 ,0
Exp/Cntr=0.3,0.1

Type RM Length L Ch R = 1 ,11022   ,158.3,158.3,158.3
XS GIS Cut Line= 3
 2118002.4781709376423.0881014142118024.76727193376092.180678403
2118019.62363323 375986.73608506
#Sta/Elev= 30
       0 2552.36     9.8 2547.93    19.6 2545.11    39.4 2535.56    45.9 2534.35
    55.8 2529.98    78.8 2521.97   105.1 2514.98   134.7 2510.24   174.2 2508.29
   190.6 2505.19   226.8 2505.94   253.1 2502.38     263  2503.3   273.4 2501.32
   289.3 2500.31     309 2501.81   312.3 2503.22   315.5 2509.28   318.9 2533.63
   321.6 2547.11   322.2 2549.55   325.4  2553.8   335.3 2555.44   341.1  2559.1
   345.2 2560.37   361.6 2562.88   379.1 2564.35   417.1  2564.1   437.2 2566.48
#Mann= 3 ,-1 , 0
       0      .1       0   273.4    .045       0     309      .1       0
Bank Sta=273.4,309
XS Rating Curve= 0 ,0
Exp/Cntr(USF)=0,0
Exp/Cntr=0.3,0.1