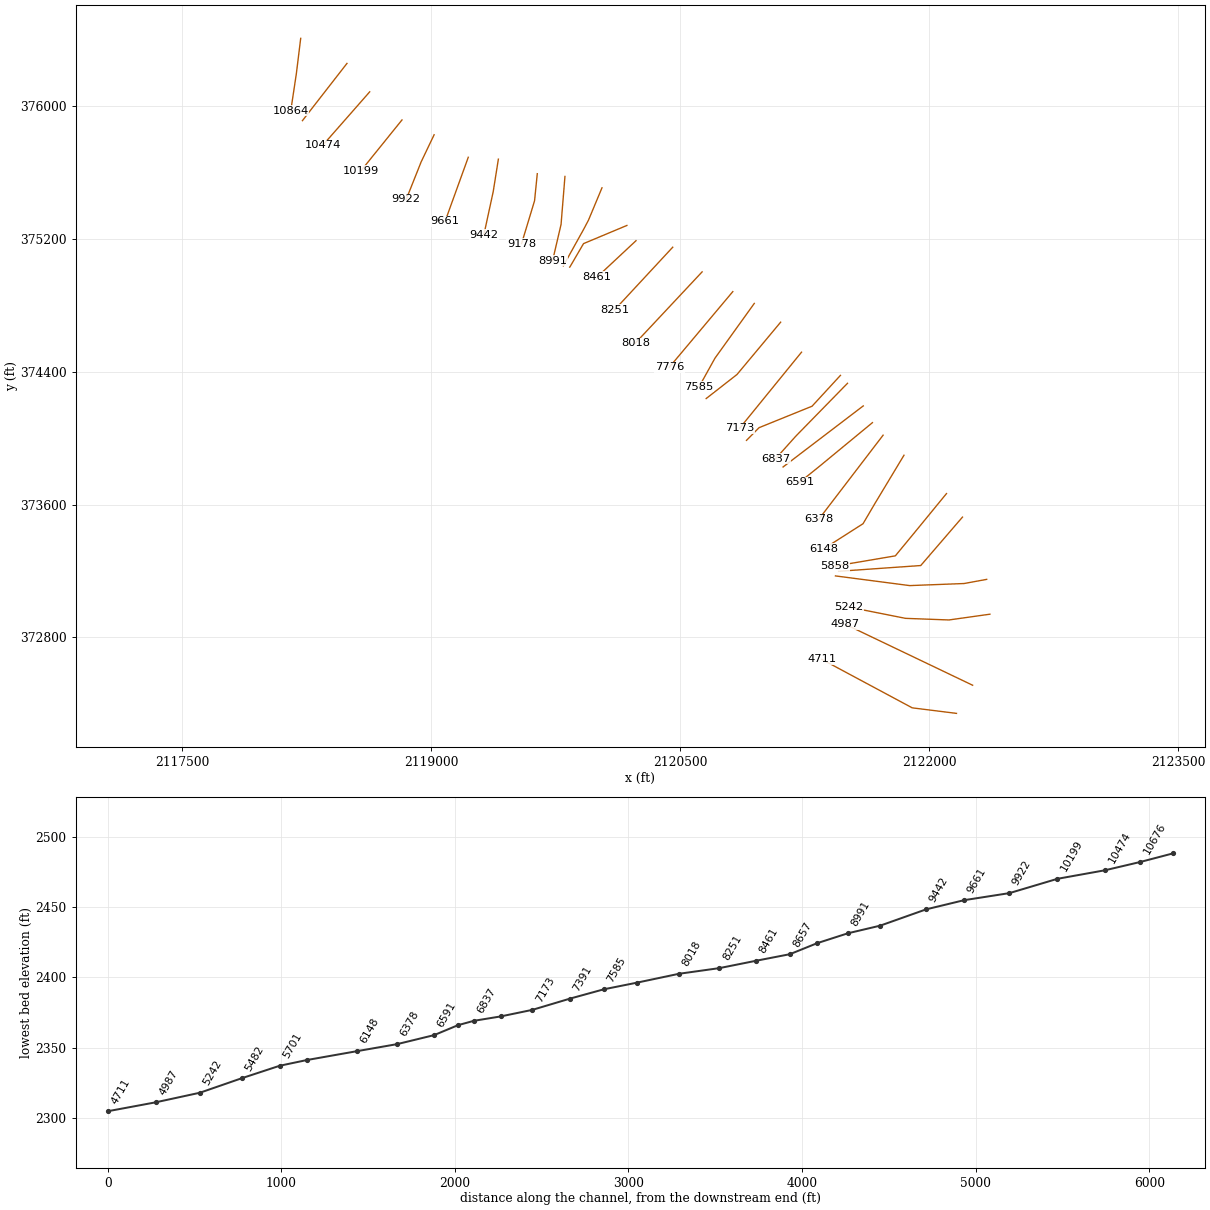
HEC-RAS study ROARINGCK.prj: ROARINGCK

--- ROARINGCK.g01 (geometry) --- (continued)

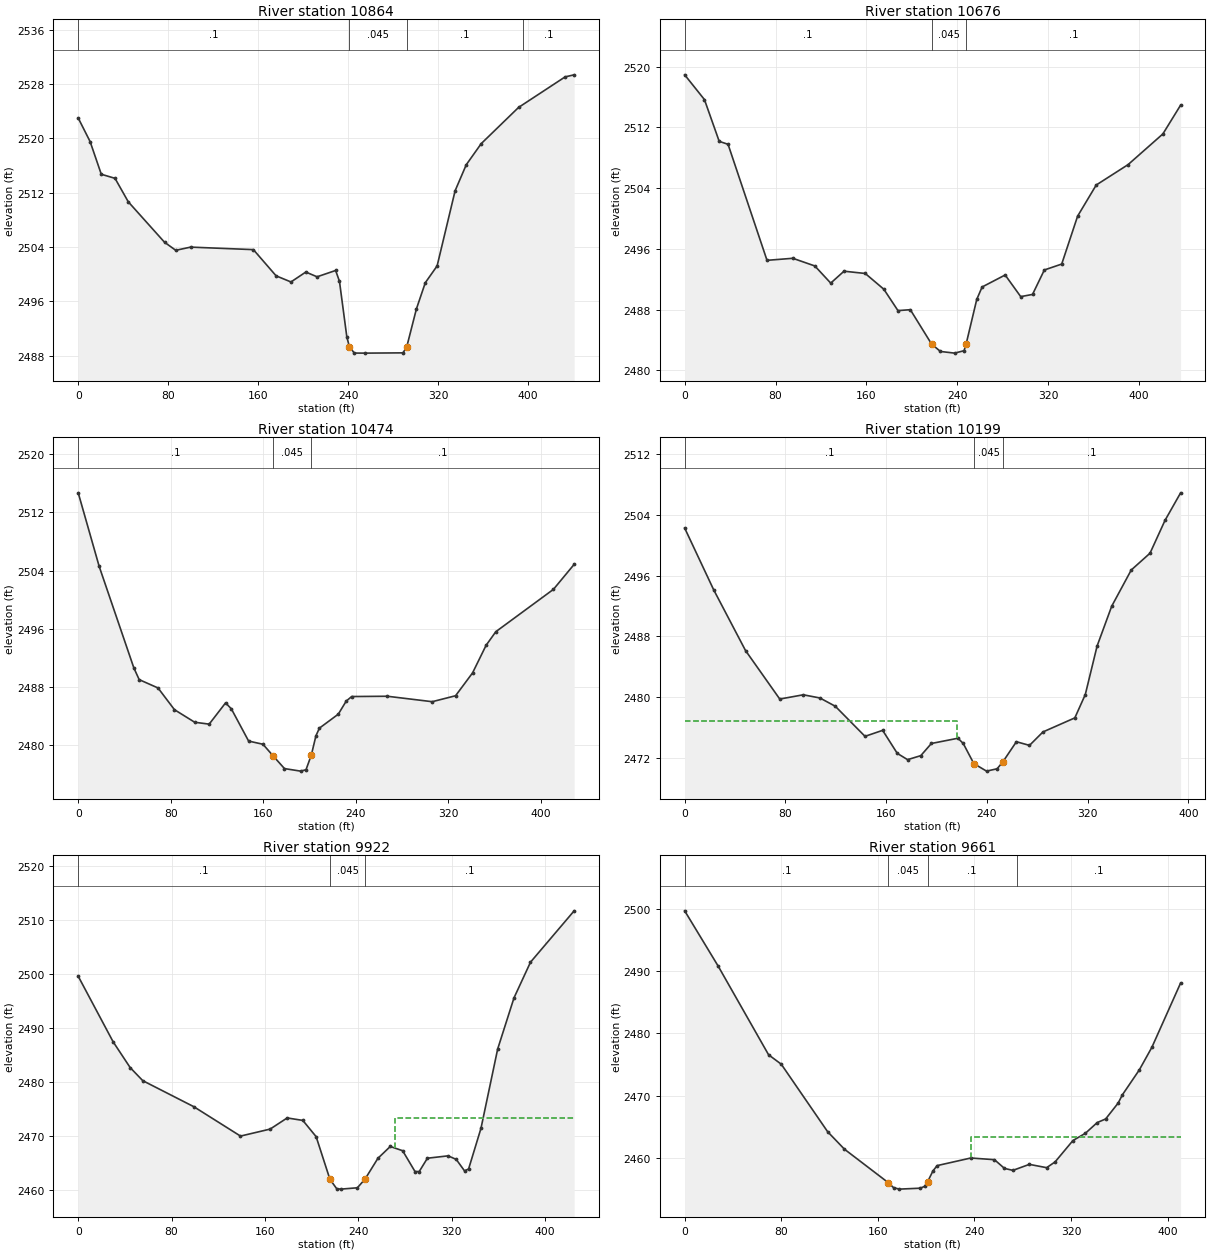
Type RM Length L Ch R = 1 ,10864   ,195.63,187.85,180.07
XS GIS Cut Line= 3
2118213.52671379376407.478507116 2118187.4850992376195.672828361
2118153.63083622375970.846506372
#Sta/Elev= 30
       0    2523    10.6 2519.52    20.5 2514.72    32.7 2514.12    44.5 2510.66
    76.7 2504.71    86.7 2503.52    99.9 2503.99   155.7 2503.62   175.9 2499.76
   189.1 2498.86   202.3 2500.32   212.3 2499.62   228.8 2500.55   232.2 2498.96
   238.8 2490.71   241.1 2489.31   245.4 2488.39   255.2 2488.38   288.6 2488.42
   291.9 2489.24   300.6 2494.89   308.5 2498.75     319 2501.22     335 2512.29
   344.9 2516.12   358.2 2519.23   391.4 2524.56   432.8 2529.06   440.8 2529.36
#Mann= 4 ,-1 , 0
       0      .1       0   241.1    .045       0   291.9      .1       0
  395.45      .1       0
Bank Sta=241.1,291.9
XS Rating Curve= 0 ,0
Exp/Cntr=0.3,0.1

Type RM Length L Ch R = 1 ,10676   ,203.53,202.63,201.74
XS GIS Cut Line= 2
2118492.17248195376256.4368144422118223.94335961375911.818737283
#Sta/Elev= 30
       0 2518.93    17.4 2515.67    30.4 2510.17    38.2 2509.78    72.5  2494.5
    95.2 2494.77   114.6 2493.76   128.6  2491.5   140.3 2493.07     159 2492.77
   175.4 2490.69   187.8 2487.88   198.7    2488   217.4 2483.48   225.2  2482.5
   237.7 2482.28     246  2482.6   247.8 2483.46   257.2 2489.36   261.9 2490.99
   282.2 2492.57   295.9 2489.72   306.3 2490.01   316.7 2493.23     332 2494.01
     346 2500.32   362.4 2504.42   390.4  2507.1   421.1 2511.15   436.7 2514.94
#Mann= 3 ,-1 , 0
       0      .1       0   217.4    .045       0   247.8      .1       0
Bank Sta=217.4,247.8
XS Rating Curve= 0 ,0
Exp/Cntr=0.3,0.1

Type RM Length L Ch R = 1 ,10474   ,274.23,274.88,275.53
XS GIS Cut Line= 2
2118629.32542288376085.4299386142118346.33911222375763.381042033
#Sta/Elev= 30
       0  2514.7    18.1 2504.58    48.1 2490.59    52.7 2488.98      69 2487.83
    83.2 2484.84   100.7 2483.11   113.2 2482.85   127.4 2485.78   132.4 2484.95
   147.3 2480.52   159.7 2480.08  168.772478.426   178.3 2476.73   192.2 2476.38
   196.9 2476.57   201.5 2478.59   205.5 2481.25   208.5  2482.3   224.8 2484.22
   231.7 2486.03   236.4 2486.65   267.2 2486.69     306 2485.94   326.2 2486.76
   340.9 2489.91   352.6 2493.71     361 2495.58   410.8 2501.41   428.7 2504.85
#Mann= 3 ,-1 , 0
       0      .1       0  168.77    .045       0   201.5      .1       0
Bank Sta=168.77,201.5
XS Rating Curve= 0 ,0
Exp/Cntr=0.3,0.1

Type RM Length L Ch R = 1 ,10199   ,272.14,276.66,281.19
XS GIS Cut Line= 2
2118823.76991588  375916.15895172118576.37408522 375609.73535195
#Sta/Elev= 30
       0 2502.27      23 2494.15    48.3 2486.15    75.5 2479.76    94.2 2480.32
   107.4  2479.9   119.6 2478.81   143.2 2474.85   157.2 2475.64   168.8 2472.61
     177 2471.78   187.5 2472.31   195.9 2473.91     217  2474.6   221.2 2473.91
   229.6 2471.26   239.7 2470.27   248.1 2470.58   252.8 2471.53   263.4 2474.14
   273.8 2473.66   284.5 2475.43   309.8 2477.28   318.1 2480.35   327.5 2486.75
   339.1 2491.99   354.6 2496.75   369.5 2498.96   381.4 2503.28   393.8 2506.91
#Mann= 3 ,-1 , 0
       0      .1       0   229.6    .045       0   252.8      .1       0
#XS Ineff= 2 , 0
          216.41 2476.83
Permanent Ineff=
       F       F
Bank Sta=229.6,252.8
XS Rating Curve= 0 ,0
Exp/Cntr=0.3,0.1

Type RM Length L Ch R = 1 ,9922    ,260.73,261.2,261.66
XS GIS Cut Line= 3
2119017.34630036375826.7493536172118939.22112855375663.554798111
2118848.94342196375436.992259115
#Sta/Elev= 30
       0  2499.6    29.9 2487.43    44.5 2482.64    55.3 2480.21      99 2475.38
     139 2469.92   164.4 2471.22     179 2473.29   192.4 2472.83   203.8 2469.81
  215.59  2461.9   221.4 2460.15     225 2460.07   239.1 2460.32  245.662461.926
   256.7 2465.79   267.3 2467.99   277.9  2467.2   288.5 2463.33   292.1 2463.34
   299.1 2465.81   316.8 2466.25   323.8 2465.59   330.9 2463.46   334.4 2463.82
     345 2471.37   359.3  2486.1   373.3  2495.6   387.4 2502.21   424.8 2511.75
#Mann= 3 ,-1 , 0
       0      .1       0  215.59    .045       0  245.66      .1       0
#XS Ineff= 2 , 0
                          271.36         2473.19
Permanent Ineff=
       F       F
Bank Sta=215.59,245.66
XS Rating Curve= 0 ,0
Exp/Cntr=0.3,0.1

Type RM Length L Ch R = 1 ,9661    ,216.94,218.96,220.99
XS GIS Cut Line= 2
2119223.07521963375691.3326296962119083.31828129375305.047969192
#Sta/Elev= 30
       0 2499.65    27.7  2490.8    69.5 2476.57      80 2475.06   118.4 2464.24
   132.3 2461.44  168.732456.055     173 2455.27   177.7 2455.03   195.1 2455.18
   198.7 2455.47   201.2  2456.2   205.6 2457.93   209.1  2458.8     237 2460.02
   256.6 2459.75   264.9 2458.35   271.9 2458.04   285.5    2459   299.8 2458.47
   306.8 2459.39   321.6 2462.82   331.9 2463.98   341.7  2465.7   348.7 2466.28
   359.1 2468.84   362.6 2470.16   376.6 2474.15     387 2477.77   410.8 2488.08
#Mann= 4 ,-1 , 0
       0      .1       0  168.73    .045       0   201.2      .1       0
  275.15      .1       0
#XS Ineff= 2 , 0
                          236.84         2463.32
Permanent Ineff=
       F       F
Bank Sta=168.73,201.2
XS Rating Curve= 0 ,0
Exp/Cntr=0.3,0.1

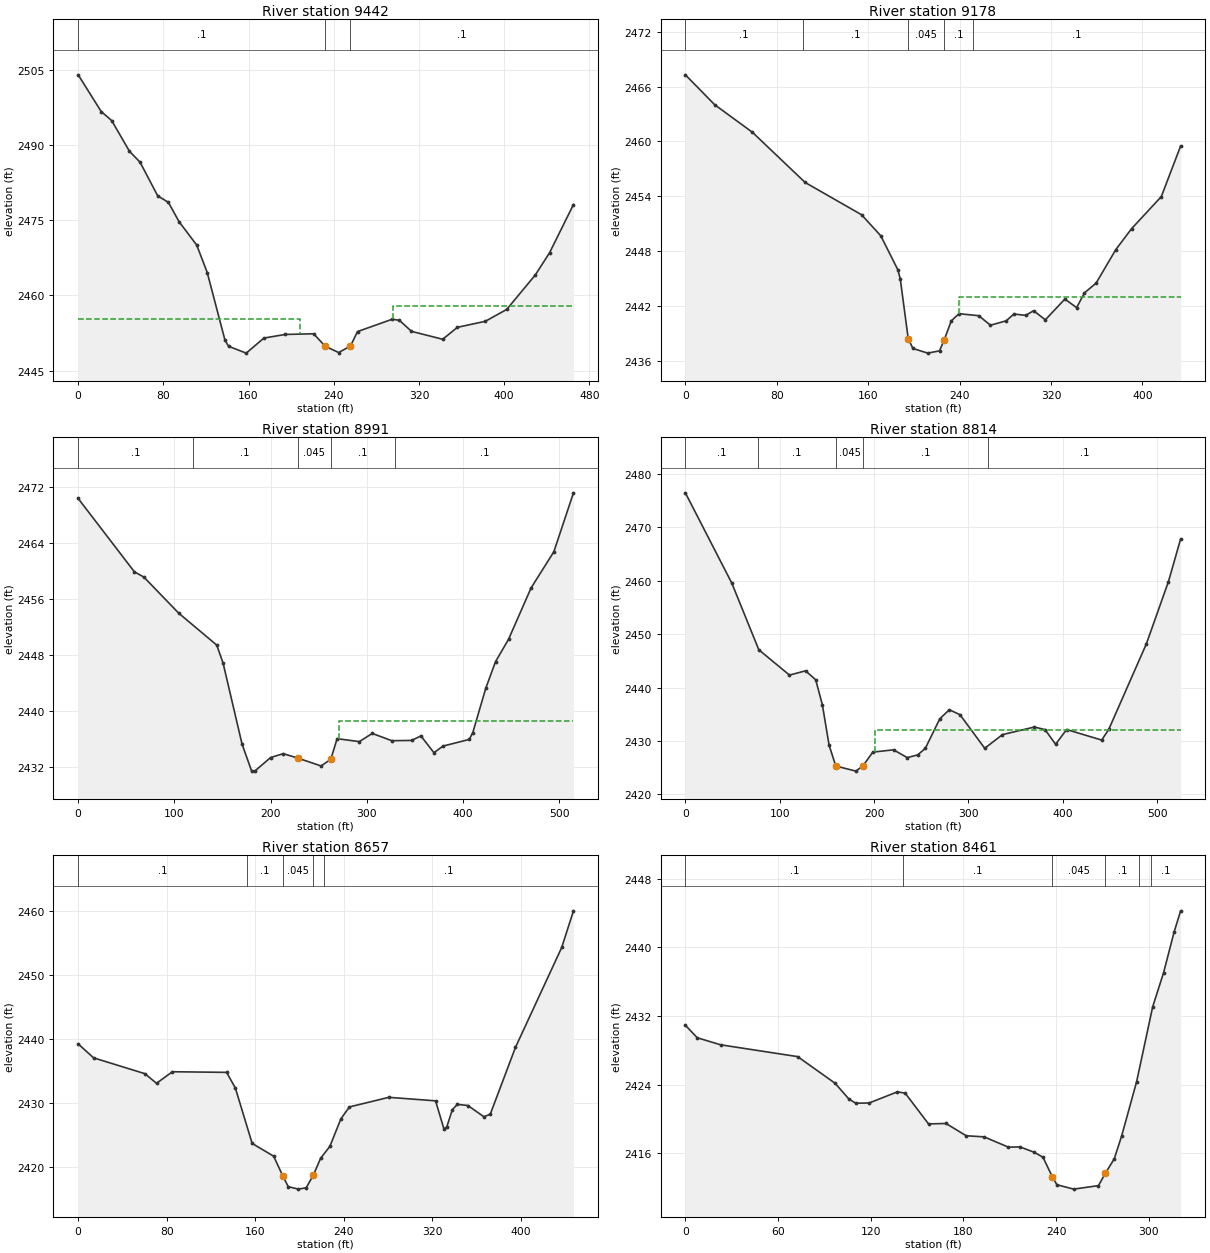
Type RM Length L Ch R = 1 ,9442    ,265.31,264.3,262.99
XS GIS Cut Line= 3
2119404.49906936 375680.047875362119373.24880379375483.867165372
2119316.82536021375223.450691447
#Sta/Elev= 30
       0  2504.1    21.6 2496.77    31.5 2494.95    48.1 2488.84    58.1 2486.64
    74.7 2479.91    84.7 2478.62    94.7 2474.76   111.3 2470.08   121.2 2464.58
   137.8 2451.11   141.2 2449.85   157.8 2448.48   174.4 2451.49   194.3 2452.21
   221.1 2452.35     232 2449.85   244.6  2448.6   255.7  2449.9   262.3 2452.79
     295 2455.26   301.7 2455.03     313 2452.83   342.3 2451.25   356.1 2453.64
   382.3 2454.84   402.4 2457.21   429.3 2464.11   442.7 2468.56   465.1 2478.18
#Mann= 3 , 0 , 0
       0      .1       0     232    .045       0   255.7      .1       0
#XS Ineff= 2 , 0
          208.23  2455.3   295.7         2457.85
Permanent Ineff=
       F       F
Bank Sta=232,255.7
XS Rating Curve= 0 ,0
Exp/Cntr=0.3,0.1

Type RM Length L Ch R = 1 ,9178    ,183.47,186.37,189.57
XS GIS Cut Line= 3
 2119638.8739287375592.3741662062119622.38085145375429.179938778
 2119544.2560077375171.367134199
#Sta/Elev= 30
       0 2467.28    25.6 2464.02    58.6 2461.01   104.8 2455.52   154.2 2451.99
     171 2449.69     186 2445.96   188.1 2444.94     195 2438.46   199.1 2437.38
   212.1 2436.87   222.4 2437.12   226.6 2438.35   232.7  2440.4   239.5 2441.18
   256.7 2440.96     267 2439.92   280.7  2440.4   287.5 2441.14   297.8    2441
   304.7  2441.5     315 2440.51   332.1 2442.78   342.4 2441.84   349.2 2443.45
   359.4 2444.52   376.7 2448.19   390.4 2450.46   416.5 2453.98   433.4 2459.51
#Mann= 5 ,-1 , 0
       0      .1       0  102.86      .1       0     195    .045       0
   226.6      .1       0  251.26      .1       0
#XS Ineff= 2 , 0
                          239.67            2443
Permanent Ineff=
       F       F
Bank Sta=195,226.6
XS Rating Curve= 0 ,0
Exp/Cntr=0.3,0.1

Type RM Length L Ch R = 1 ,8991    ,182.14,177.36,172.59
XS GIS Cut Line= 3
2119805.54059014375575.8810889422119782.10297295375286.818674952
2119730.88785228375068.068784371
#Sta/Elev= 30
       0  2470.4    58.4 2459.92    68.3 2459.16   104.5    2454     144 2449.44
   150.6 2446.86   170.3 2435.28   180.2 2431.45   183.5 2431.42   199.9 2433.36
   213.1 2433.92  227.932433.298   252.4 2432.16   262.5 2433.11   269.1 2436.06
   292.2 2435.64   305.6 2436.81   325.9 2435.77   346.4 2435.81   356.2 2436.45
   369.7 2434.05   379.1    2435   406.4 2435.95   410.1 2436.94   423.6 2443.28
   433.7 2447.07   447.2 2450.26   470.7 2457.63   494.3 2462.78   514.7 2471.21
#Mann= 5 ,-1 , 0
       0      .1       0  119.04      .1       0  227.93    .045       0
   262.5      .1       0  329.73      .1       0
#XS Ineff= 2 , 0
                          270.63         2438.61
Permanent Ineff=
       F       F
Bank Sta=227.93,262.5
XS Rating Curve= 0 ,0
Exp/Cntr=0.3,0.1

Type RM Length L Ch R = 1 ,8814    ,168.89,156.31,143.73
XS GIS Cut Line= 4
 2120028.6310232375507.3047825252119947.03374547375311.992181033
2119916.65158838375254.7006289512119795.99205279375037.686627284
#Sta/Elev= 30
       0 2476.48    49.2 2459.57    77.8 2447.09   110.3 2442.34   127.4 2443.14
   138.1 2441.46   145.2 2436.76   152.3  2429.2   159.4 2425.31   180.8 2424.35
   188.4 2425.39   198.6 2427.91   220.6 2428.34   235.1 2426.88   246.2 2427.39
   254.3 2428.63   269.6 2434.16   279.7 2435.85     291 2434.92   317.2 2428.63
     336 2431.19   369.8 2432.61   381.1 2432.13   392.3 2429.38     404 2432.14
   441.1 2430.17   448.6 2432.16   488.5  2448.2   511.9 2459.87   524.8 2467.86
#Mann= 5 ,-1 , 0
       0      .1       0   77.12      .1       0   159.4    .045       0
   188.4      .1       0  320.98      .1       0
#XS Ineff= 2 , 0
                          200.68         2431.98
Permanent Ineff=
       F       F
Bank Sta=159.4,188.4
XS Rating Curve= 0 ,0
Exp/Cntr=0.3,0.1

Type RM Length L Ch R = 1 ,8657    ,191.05,196.39,201.73
XS GIS Cut Line= 4
2120178.80460736375280.7422435282119917.51969686375171.367134199
2119835.92241913 375031.61019586 2119834.1865302375029.874306947
#Sta/Elev= 30
       0 2439.23    13.9 2437.05    60.2 2434.58    70.8 2433.07    85.1 2434.88
   134.1 2434.78     142 2432.34   157.2 2423.67   176.6 2421.68   184.8 2418.62
   189.8 2416.92   198.9 2416.53     206 2416.74   212.4 2418.69   219.1 2421.37
   227.4 2423.21   237.4 2427.53   245.1 2429.38   280.7 2430.88   322.9 2430.33
   330.5 2425.91     333 2426.24   338.1 2428.96   342.6 2429.78   352.1  2429.6
   366.5 2427.85   372.3 2428.23   395.1 2438.69   436.9 2454.31   447.5 2460.03
#Mann= 5 ,-1 , 0
       0      .1       0  152.49      .1       0   184.8    .045       0
   212.4      .1       0  222.12      .1       0
Bank Sta=184.8,212.4
XS Rating Curve= 0 ,0
Exp/Cntr=0.3,0.1

Type RM Length L Ch R = 1 ,8461    ,209.23,210.27,211.31
XS GIS Cut Line= 2
2120233.49216205375188.7283199432119999.11730272374969.978429362
#Sta/Elev= 30
       0 2430.91     7.7 2429.45    22.8 2428.63    72.7 2427.25    96.9 2424.15
   105.8 2422.32   110.3 2421.82     119 2421.85   137.3 2423.15   142.3 2422.99
   157.4 2419.41   168.7 2419.46   181.8 2418.03   193.4  2417.9   209.1  2416.7
   216.6 2416.73   225.9  2416.1   231.5 2415.52   237.5 2413.26   240.5 2412.32
   251.4 2411.81   267.4 2412.22   271.9 2413.67   277.6 2415.33   282.4    2418
   292.1 2424.33   302.5 2433.06   309.5    2437   316.4 2441.79   320.6 2444.24
#Mann= 6 ,-1 , 0
       0      .1       0  141.07      .1       0   237.5    .045       0
   271.9      .1       0  293.79      .1       0  301.12      .1       0
Bank Sta=237.5,271.9
XS Rating Curve= 0 ,0
Exp/Cntr=0.3,0.1

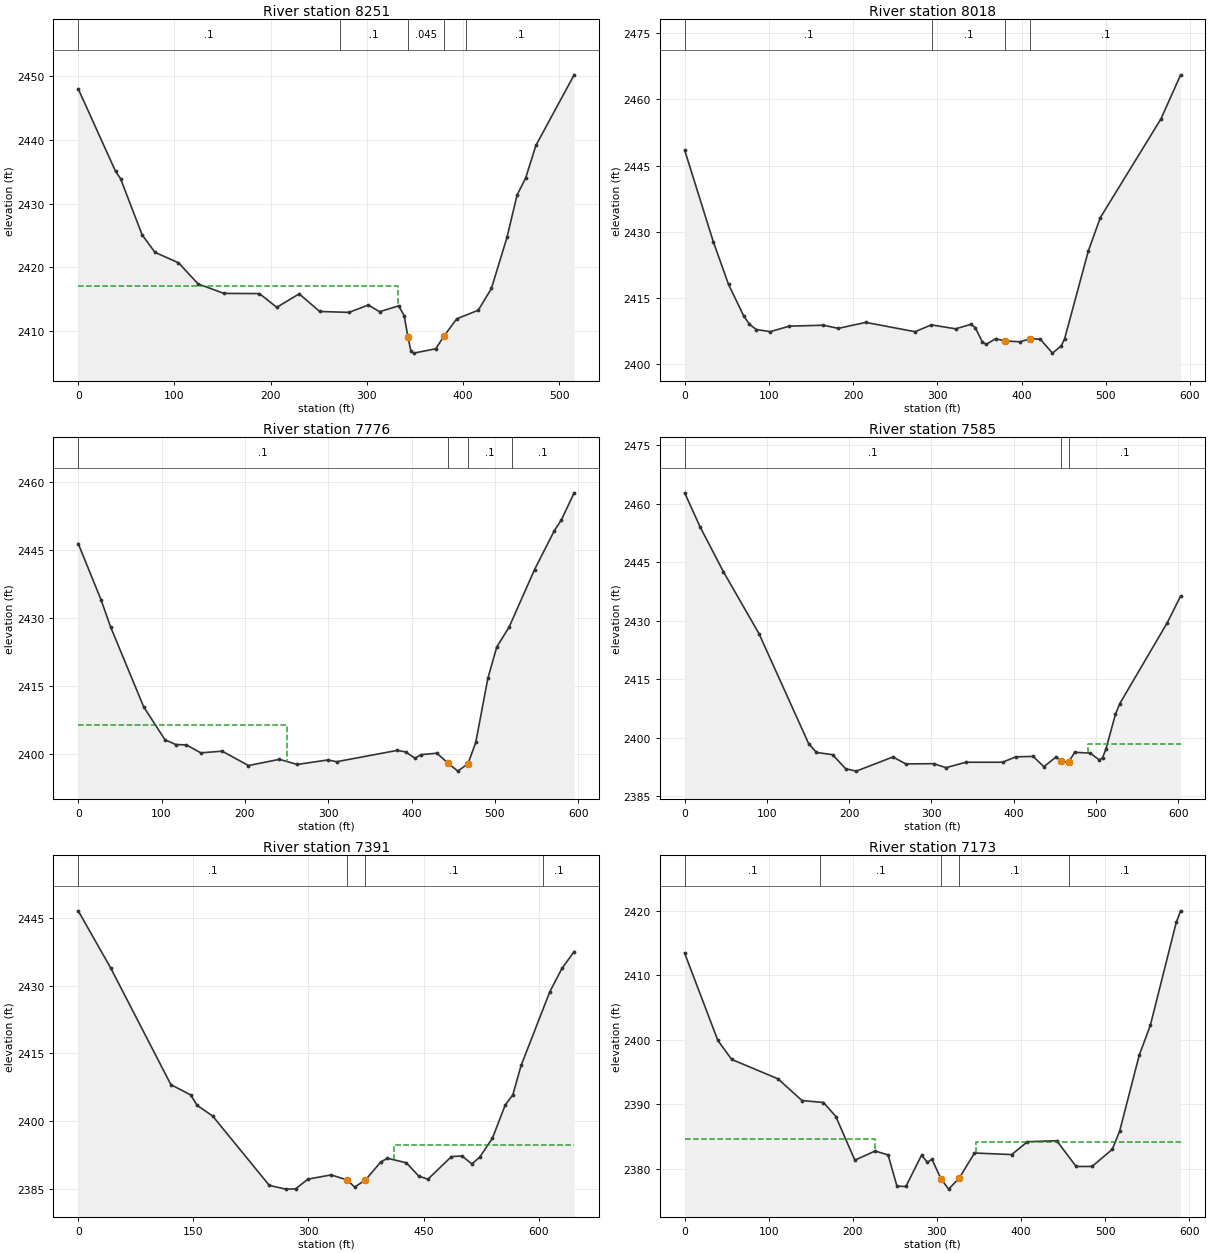
Type RM Length L Ch R = 1 ,8251    ,233.06,232.98,232.89
XS GIS Cut Line= 2
2120454.84605005375149.6660621172120104.15186954374772.061830446
#Sta/Elev= 30
       0 2447.97    38.8 2435.05      44 2433.91    66.4 2425.11    79.8 2422.36
   104.2 2420.74   124.6 2417.42   151.5 2415.94   188.3 2415.91   206.3 2413.76
   229.6 2415.87   250.9 2413.11   281.3 2412.97   301.5 2414.12   313.1 2413.07
   332.9    2414   338.7 2412.46   342.6 2409.12   345.6 2406.99   348.5 2406.59
   371.5 2407.27   379.8 2409.21   393.3 2411.96   415.7 2413.31   429.3 2416.71
   445.5  2424.7     456 2431.34   464.9 2434.01   475.6 2439.12   515.3 2450.16
#Mann= 5 ,-1 , 0
       0      .1       0  271.62      .1       0   342.6    .045       0
   379.8      .1       0  403.16      .1       0
#XS Ineff= 2 , 0
          332.43 2417.11
Permanent Ineff=
       F       F
Bank Sta=342.6,379.8
XS Rating Curve= 0 ,0
Exp/Cntr=0.3,0.1

Type RM Length L Ch R = 1 ,8018    ,241.22,242.01,242.81
XS GIS Cut Line= 2
2120631.92935729375001.2283668672120229.15161955374571.540906027
#Sta/Elev= 30
       0 2448.52    33.9 2427.83    52.1  2418.1    70.1 2410.98    76.9 2409.09
      85  2407.9   101.6 2407.42   124.4 2408.66   164.5 2408.87   182.5 2408.16
     215 2409.51   273.6  2407.4   292.8 2408.95   321.7 2408.06   339.9 2409.06
     345 2408.33   353.4 2405.12   357.9 2404.53   369.5 2405.83  379.862405.315
   398.3 2405.12  410.342405.803   422.3 2405.71   436.7 2402.55   447.1 2404.19
   451.1 2405.77   479.3 2425.68   493.5 2433.22   565.5 2455.59   588.9 2465.58
#Mann= 4 ,-1 , 0
       0      .1       0  293.64      .1       0  379.86    .045       0
  410.34      .1       0
Bank Sta=379.86,410.34
XS Rating Curve= 0 ,0
Exp/Cntr=0.3,0.1

Type RM Length L Ch R = 1 ,7776    ,187.5,190.36,193.21
XS GIS Cut Line= 2
2120816.82531297374882.3047201932120434.01275837374426.575644776
#Sta/Elev= 30
       0 2446.38    27.3 2434.05    38.9    2428    78.5 2410.42   104.1 2403.14
   117.1 2402.08   129.8    2402   147.1 2400.25   172.8 2400.62   204.3 2397.45
   241.5 2398.82   262.8 2397.69   299.8 2398.69     310 2398.29   382.8 2400.79
   392.9 2400.46   404.2 2399.06   411.5 2399.86   430.4 2400.17   444.1 2397.94
   455.6 2396.22  467.782397.861   477.1 2402.54   491.6 2416.65   502.3 2423.58
   517.1 2427.96   547.7 2440.66   571.3 2449.19   579.9 2451.63   595.2 2457.57
#Mann= 4 ,-1 , 0
       0      .1       0   444.1    .045       0  467.78      .1       0
   520.6      .1       0
#XS Ineff= 2 , 0
          250.93 2406.36
Permanent Ineff=
       F       F
Bank Sta=444.1,467.78
XS Rating Curve= 0 ,0
Exp/Cntr=0.3,0.1

Type RM Length L Ch R = 1 ,7585    ,197.34,194.46,191.59
XS GIS Cut Line= 3
2120946.16560546374811.1240882872120709.18642062374481.263199449
2120613.70039111 374309.38821511
#Sta/Elev= 30
       0 2462.82    18.8 2454.06      47 2442.64    90.4  2426.7   150.7 2398.54
   160.2 2396.28   179.7 2395.72   195.7  2392.1   208.6  2391.5   253.1 2395.13
   268.8 2393.35   302.6 2393.41   317.7 2392.39   341.9 2393.78   386.4 2393.78
   402.5 2395.17   423.6 2395.27   436.6 2392.64   451.6 2395.16   457.7 2393.99
   466.6  2393.8   474.1 2396.32   492.9 2396.13   504.1 2394.35   507.9 2394.95
     512 2397.15   523.6 2406.08   528.8 2408.78   586.7 2429.58   602.8 2436.38
#Mann= 3 , 0 , 0
       0      .1       0   457.7    .045       0   466.6      .1       0
#XS Ineff= 2 , 0
                          489.64         2398.34
Permanent Ineff=
       F       F
Bank Sta=457.7,466.6
XS Rating Curve= 0 ,0
Exp/Cntr=0.3,0.1

Type RM Length L Ch R = 1 ,7391    ,217.48,217.64,217.81
XS GIS Cut Line= 3
2121105.01961845374698.2768730372120841.99881905374383.172844455
2120656.23508295374238.207583204
#Sta/Elev= 30
       0 2446.69    42.1 2434.06   120.7 2408.09   146.4  2405.8   154.9 2403.49
   175.2  2401.1   248.9 2385.71   270.3 2384.87   283.1 2384.92   299.3 2387.09
   329.5 2388.03   350.5  2386.9     360 2385.34   373.8 2386.82   394.2 2390.91
   402.8 2391.72   427.4 2390.73   443.5  2387.8   455.5 2387.06   486.2 2392.09
   499.9 2392.24   512.9 2390.46   523.1 2391.99   539.7 2396.21   556.3 2403.56
   566.2 2405.81     577 2412.34   614.4 2428.72   630.2 2433.89   646.1 2437.64
#Mann= 4 ,-1 , 0
       0      .1       0   350.5    .045       0   373.8      .1       0
  605.52      .1       0
#XS Ineff= 2 , 0
                             412         2394.77
Permanent Ineff=
       F       F
Bank Sta=350.5,373.8
XS Rating Curve= 0 ,0
Exp/Cntr=0.3,0.1

Type RM Length L Ch R = 1 ,7173    ,189.27,181.68,174.08
XS GIS Cut Line= 2
2121230.88780504374517.721459866 2120858.4918963374060.256167442
#Sta/Elev= 30
       0  2413.4    39.4  2399.9    55.9 2396.94   110.9 2393.94   139.5 2390.57
   165.1 2390.26   179.8 2388.09   202.4 2381.32   226.5 2382.74     242 2382.13
   252.5 2377.29   263.1 2377.24   281.7 2382.08   288.7    2381   294.1 2381.45
     305  2378.4     314 2376.83   326.7 2378.57   344.7 2382.43     389 2382.19
   407.7 2384.18   442.6 2384.33   465.6 2380.34   484.6 2380.35   508.6    2383
   517.3 2385.79   540.6 2397.56   553.9 2402.24   584.7 2418.19   589.9 2419.98
#Mann= 5 ,-1 , 0
       0      .1       0  161.38      .1       0     305    .045       0
   326.7      .1       0  457.63      .1       0
#XS Ineff= 2 , 0
          226.97 2384.57  346.35         2384.07
Permanent Ineff=
       F       F
Bank Sta=305,326.7
XS Rating Curve= 0 ,0
Exp/Cntr=0.3,0.1

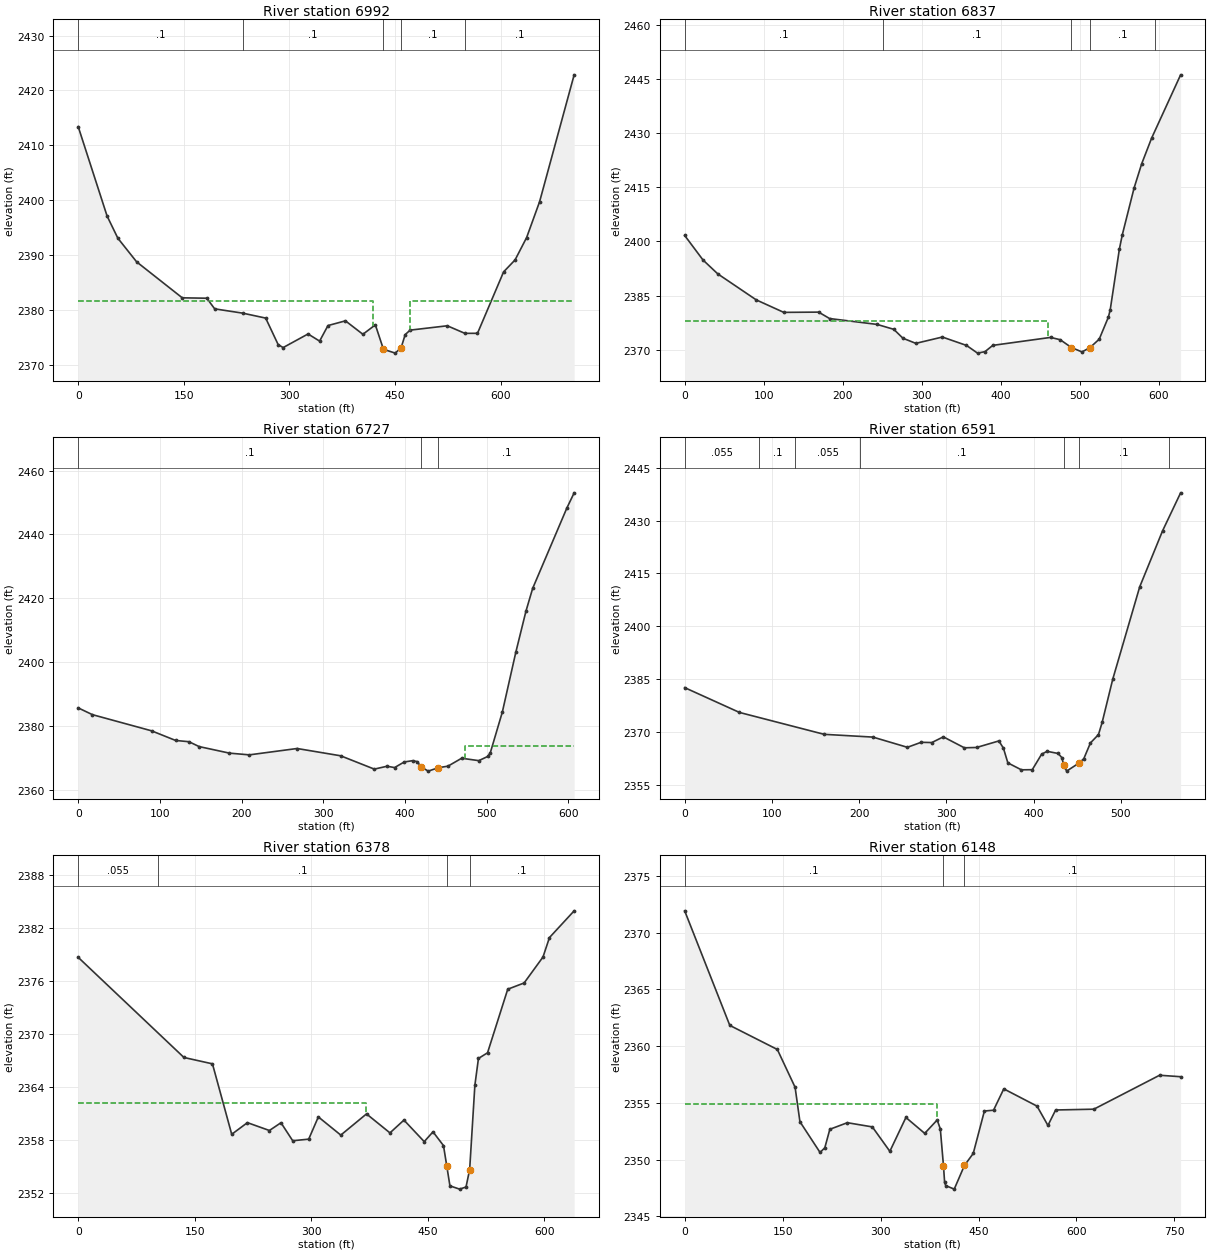
Type RM Length L Ch R = 1 ,6992    ,147.4,154.29,161.18
XS GIS Cut Line= 4
2121465.26266438374377.9645215272121294.25578853374192.200785443
2120974.81154555374062.8604929452120899.29069921373986.471538112
#Sta/Elev= 30
       0 2413.41      41 2397.14    56.3  2393.1      83 2388.79   147.8 2382.24
   182.6 2382.17   193.9 2380.23   233.7 2379.45   266.3 2378.55     284 2373.73
   291.1 2373.18   326.5 2375.66   342.9 2374.36   354.8 2377.19   379.6 2378.05
   404.4  2375.6   422.1 2377.32   433.6 2372.87   450.4 2372.17   458.8 2373.19
   464.5 2375.55   471.6 2376.36   524.3 2377.15   549.3 2375.77   567.2 2375.78
   604.3 2386.97   620.6 2389.15     637 2393.22   655.4 2399.74   704.5 2422.85
#Mann= 5 ,-1 , 0
       0      .1       0   233.7      .1       0   433.6    .045       0
   458.8      .1       0   549.3      .1       0
#XS Ineff= 2 , 0
          419.09 2381.72  470.64         2381.62
Permanent Ineff=
       F       F
Bank Sta=433.6,458.8
XS Rating Curve= 0 ,0
Exp/Cntr=0.3,0.1

Type RM Length L Ch R = 1 ,6837    ,91.8,91.8,91.8
XS GIS Cut Line= 3
2121507.79768428374330.2215067892121197.03354204374012.513152704
2121074.63778946373876.228320286
#Sta/Elev= 30
       0 2401.66    23.2 2394.86    41.9 2391.01    90.6  2383.8   125.4 2380.34
   169.5 2380.41   183.4 2378.63   243.5    2377   264.6 2375.64   276.2 2373.17
   292.5 2371.75   326.1  2373.5   356.6 2371.18   370.6 2369.04     380 2369.45
   389.9 2371.19   463.1  2373.4   475.2 2372.76   489.5 2370.58   502.8 2369.37
     513 2370.59   524.6 2372.91   536.2 2379.03   538.5 2381.04   550.1 2397.88
   553.8 2401.85   568.7 2414.81   578.3 2421.52   590.9 2428.65   627.6  2446.2
#Mann= 5 ,-1 , 0
       0      .1       0  250.98      .1       0   489.5    .045       0
     513      .1       0  595.58      .1       0
#XS Ineff= 2 , 0
          460.26 2378.05
Permanent Ineff=
       F       F
Bank Sta=489.5,513
XS Rating Curve= 0 ,0
Exp/Cntr=0.3,0.1

Type RM Length L Ch R = 1 ,6727    ,137.8,137.8,137.8
XS GIS Cut Line= 2
2121602.62670413374194.0291264242121119.69618177373826.354211968
#Sta/Elev= 30
       0 2385.73    17.4 2383.61    89.7 2378.56   119.2 2375.54   135.6 2375.14
     148 2373.62   185.1 2371.57   209.4 2371.03   267.9 2373.02   321.2 2370.74
   362.4 2366.57     378 2367.47   387.2 2367.05     399  2368.8   409.2 2369.21
   414.6 2368.93   420.1 2367.21   428.4 2365.94   440.8 2367.01   452.5 2367.49
   469.3 2369.97   490.3 2369.22   501.3 2370.54   504.4 2371.71   519.1 2384.42
   535.6 2403.14     548 2415.99   556.2 2423.11     598 2448.23     607 2453.03
#Mann= 3 ,-1 , 0
       0      .1       0   420.1    .045       0   440.8      .1       0
#XS Ineff= 1 ,-1
   473.4606.9652 2373.82
Permanent Ineff=
       F
Bank Sta=420.1,440.8
XS Rating Curve= 0 ,0
Exp/Cntr(USF)=0,0
Exp/Cntr=0.3,0.1

Type RM Length L Ch R = 1 ,6591    ,209.28,212.95,216.63
XS GIS Cut Line= 3
2121657.97126845374093.2423219532121337.65858889373829.353414029
2121217.86683372373732.999276027
#Sta/Elev= 30
       0 2382.56    62.8 2375.51   159.9 2369.29   215.9  2368.5   255.4  2365.6
   271.1 2367.02   283.4 2366.95   296.6 2368.57   320.7 2365.46   334.7 2365.55
   360.3 2367.41   365.5 2365.36   370.6 2361.17   386.1  2359.2   398.6 2359.24
   409.3 2363.64   415.6 2364.46   428.2 2363.85   432.4  2362.7   434.9 2360.45
     438 2358.83   452.3 2361.15   457.7 2362.37   465.3 2366.85   474.5 2369.21
   478.7 2372.66   490.9 2384.98   521.8 2411.21     548 2427.12   568.7 2437.92
#Mann= 7 ,-1 , 0
       0    .055       0   85.27      .1       0  127.06    .055       0
  200.87      .1       0   434.9    .045       0   452.3      .1       0
  555.42      .1       0
Bank Sta=434.9,452.3
XS Rating Curve= 0 ,0
Exp/Cntr=0.3,0.1

Type RM Length L Ch R = 1 ,6378    ,228.73,230.57,232.42
XS GIS Cut Line= 2
2121722.20736045374017.7214756162121334.18648297373510.776951447
#Sta/Elev= 30
       0 2378.66   136.1 2367.32   172.8  2366.6   197.6 2358.62   217.8 2359.94
   246.1 2359.05     261 2359.93   276.1 2357.89   296.7 2358.07   309.1 2360.59
     338 2358.53   371.1 2360.93   401.3 2358.78   419.3 2360.23   445.4 2357.79
   456.7  2358.9   470.2 2357.34   474.4 2355.05   478.5 2352.78   490.9 2352.41
   499.2 2352.65   503.9 2354.63   510.6 2364.17   515.2 2367.21   526.9 2367.85
   552.9 2375.05     574 2375.76   598.3  2378.7   606.6  2380.9   638.4 2383.93
#Mann= 4 ,-1 , 0
       0    .055       0  102.74      .1       0   474.4    .045       0
   503.9      .1       0
#XS Ineff= 2 , 0
           370.8 2362.14
Permanent Ineff=
       F       F
Bank Sta=474.4,503.9
XS Rating Curve= 0 ,0
Exp/Cntr=0.3,0.1

Type RM Length L Ch R = 1 ,6148    ,292.49,290.01,287.54
XS GIS Cut Line= 4
2121848.07521895 373897.061611952121671.86002022373604.527092025
 2121601.5474968 373484.735336872121366.30452895373334.561752692
#Sta/Elev= 30
       0 2371.92    69.1 2361.83   141.9 2359.71   169.1 2356.38   176.5 2353.35
   207.3 2350.64   214.6 2351.05   222.3 2352.68   249.1 2353.26   287.4 2352.89
   314.2 2350.74   338.8 2353.72   367.6 2352.32   386.7  2353.5   391.5 2352.71
   396.3 2349.49   398.1    2348   399.8 2347.72   412.8 2347.41   428.5  2349.5
   441.9 2350.55     459 2354.29     473 2354.36   488.7 2356.24   539.6 2354.72
   556.3 2353.02   568.1 2354.38   626.6 2354.45   727.3 2357.44   759.5 2357.31
#Mann= 3 ,-1 , 0
       0      .1       0   396.3    .045       0   428.5      .1       0
#XS Ineff= 2 , 0
          386.19 2354.87
Permanent Ineff=
       F       F
Bank Sta=396.3,428.5
XS Rating Curve= 0 ,0
Exp/Cntr=0.3,0.1

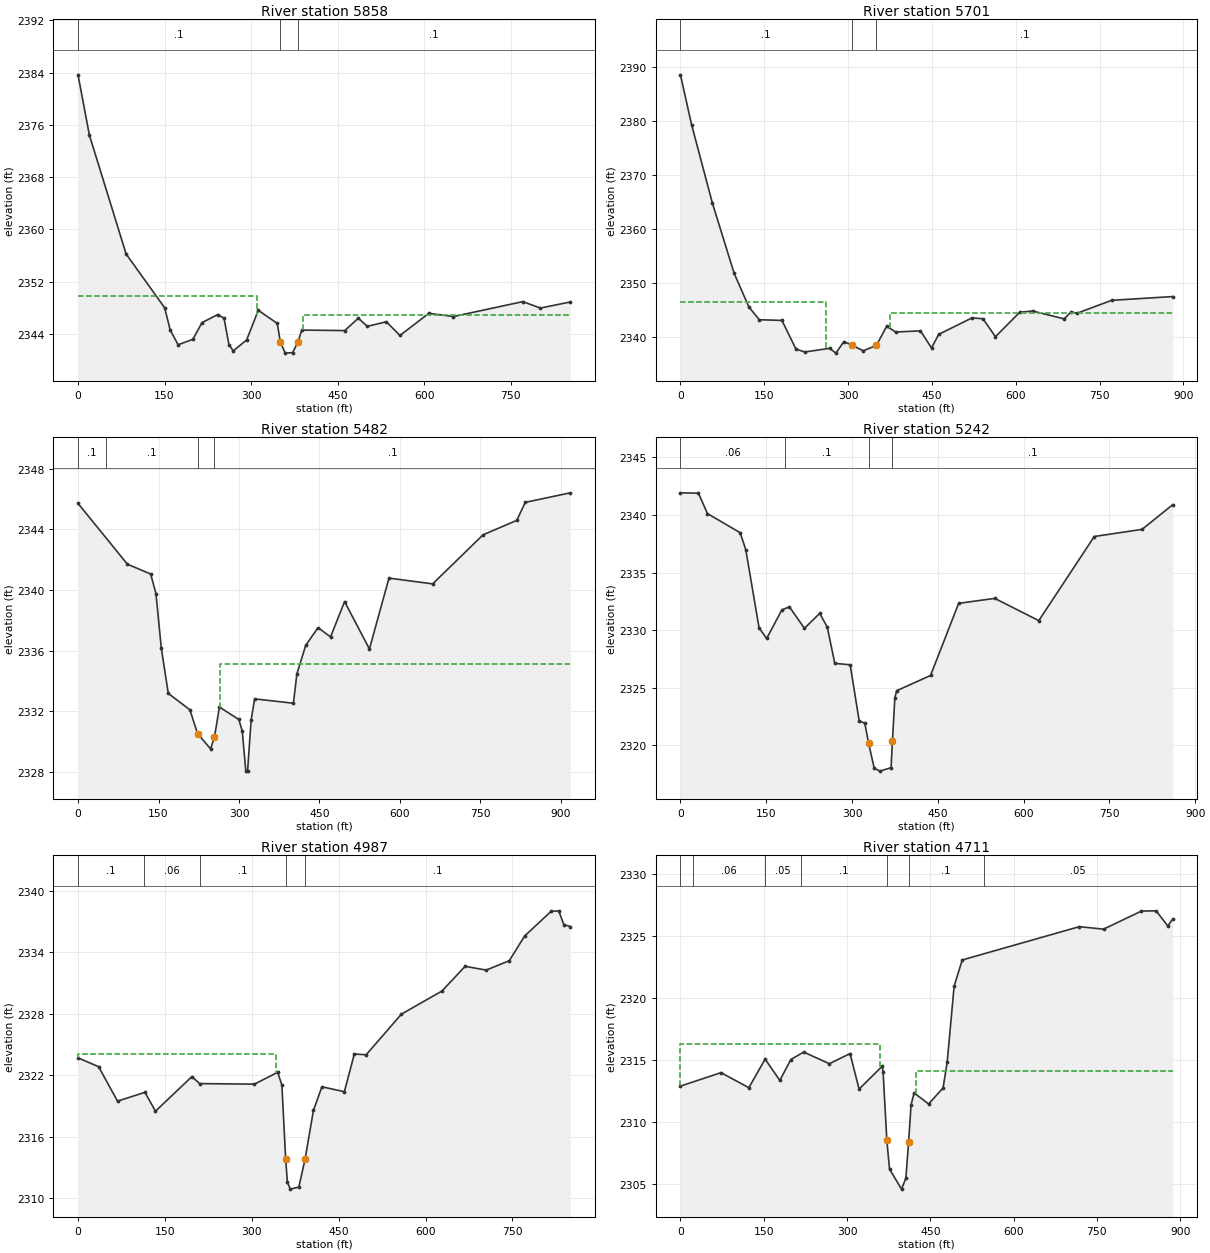
Type RM Length L Ch R = 1 ,5858    ,156.91,156.6,156.28
XS GIS Cut Line= 4
2122104.15180653373666.1588585382121902.76277363373420.499244869
2121795.99198979 373291.158952372121433.14461836373229.526857778
#Sta/Elev= 30
       0 2383.66    19.6 2374.46    83.4 2356.23   150.2    2348   159.8  2344.6
   173.5 2342.34   199.1 2343.17   214.9 2345.73     242 2346.95   253.1 2346.41
   261.6 2342.38   269.1  2341.4   292.4 2343.09   312.5 2347.62   345.4 2345.61
   350.8 2342.75   359.3 2341.06     372 2341.14     381  2342.7   387.9 2344.59
   462.5 2344.51   485.9 2346.41   501.5 2345.16   534.7 2345.86     558 2343.76
   608.2 2347.15   650.9 2346.66     771 2348.94   801.7 2347.96   853.4 2348.89
#Mann= 3 ,-1 , 0
       0      .1       0   350.8    .045       0     381      .1       0
#XS Ineff= 2 , 0
          309.56 2349.74  389.36         2346.91
Permanent Ineff=
       F       F
Bank Sta=350.8,381
XS Rating Curve= 0 ,0
Exp/Cntr=0.3,0.1

Type RM Length L Ch R = 1 ,5701    ,232.14,219.35,206.57
XS GIS Cut Line= 3
2122200.50594455373524.4921471182121949.11701164373232.825735703
2121454.67246246373198.103364199
#Sta/Elev= 30
       0 2388.47      20 2379.22    57.2 2364.72    96.1 2351.74   122.4 2345.53
     141 2343.15   181.6 2343.02   206.7 2337.72   222.4 2337.18     267 2337.86
   278.2 2336.97   292.3  2339.1  306.212338.499   327.1  2337.4  350.542338.401
     369 2341.94   385.1 2340.88   429.5 2341.09   449.2 2337.93   462.1 2340.44
   521.6 2343.49   541.3 2343.33   563.6 2340.01   607.1 2344.54   630.1 2344.76
   686.5 2343.31   699.2 2344.64     709 2344.33   771.5 2346.74   880.7 2347.44
#Mann= 3 ,-1 , 0
       0      .1       0  306.21    .045       0  350.54      .1       0
#XS Ineff= 2 , 0
          260.33 2346.43  374.65         2344.47
Permanent Ineff=
       F       F
Bank Sta=306.21,350.54
XS Rating Curve= 0 ,0
Exp/Cntr=0.3,0.1

Type RM Length L Ch R = 1 ,5482    ,240.82,239.5,238.19
XS GIS Cut Line= 4
2122346.33931428 373149.492240952122210.22803795373124.492290944
2121882.45047829373111.9923159482121435.22794753373170.325532615
#Sta/Elev= 30
       0 2345.72      92 2341.71   135.4 2341.06   145.3 2339.76   155.1 2336.19
   168.2 2333.18   208.5  2332.1  222.71 2330.53     247 2329.52   254.3  2330.3
   263.5 2332.28   299.6 2331.46   306.1 2330.69   312.7 2328.05     316 2328.06
   322.6 2331.41   329.1 2332.82   401.4 2332.53   407.9 2334.47   424.3 2336.35
   447.3 2337.52   470.6 2336.91   496.8 2339.24   543.1 2336.11   579.5 2340.79
   660.9 2340.41   754.9 2343.65   817.7  2344.6   833.5 2345.79   917.4 2346.42
#Mann= 4 ,-1 , 0
       0      .1       0   51.29      .1       0  222.71    .045       0
   254.3      .1       0
#XS Ineff= 2 , 0
                          264.92          2335.1
Permanent Ineff=
       F       F
Bank Sta=222.71,254.3
XS Rating Curve= 0 ,0
Exp/Cntr=0.3,0.1

Type RM Length L Ch R = 1 ,5242    ,261.71,255.53,249.34
XS GIS Cut Line= 4
2122365.78350112372939.7702194452122118.56155464372905.047847942
 2121857.4502002 372914.769941362121514.39478397372982.825579539
#Sta/Elev= 30
       0 2341.92    31.5 2341.89    47.2 2340.12   104.4 2338.46   114.3 2336.98
   137.5  2330.2   150.8 2329.28   177.3 2331.76   190.5 2332.03   216.8 2330.16
   243.5 2331.46   256.7 2330.27   269.9 2327.12   296.8    2327   312.5 2322.14
   322.4 2321.92   328.9 2320.21   338.8 2318.03   348.6 2317.77   368.3 2318.07
  370.682320.364   374.9 2324.15   378.2 2324.75   437.3 2326.07   486.5 2332.33
   549.6 2332.76   626.6 2330.83   723.6 2338.13   807.2 2338.75   860.7 2340.89
#Mann= 4 ,-1 , 0
       0     .06       0  182.88      .1       0   328.9    .045       0
  370.68      .1       0
Bank Sta=328.9,370.68
XS Rating Curve= 0 ,0
Exp/Cntr=0.3,0.1

Type RM Length L Ch R = 1 ,4987    ,276.56,275.87,275.18
XS GIS Cut Line= 2
2122261.61704278372511.9922036082121494.95026904372878.658793122
#Sta/Elev= 30
       0 2323.71    35.5 2322.85    68.2 2319.49   115.5 2320.35   133.7 2318.51
   196.5 2321.88     210  2321.2   304.6 2321.15   344.6  2322.3   351.9 2321.08
   358.4 2313.89   361.4 2311.59   366.4 2310.91   381.2 2311.11   391.9 2313.82
   406.4 2318.58     421 2320.89   459.8 2320.41     477 2324.09   497.4 2324.01
   558.2 2327.97   628.3 2330.23   668.3 2332.64   704.6 2332.27   744.6 2333.19
   771.1  2335.6   816.5 2337.99   829.9 2338.05   838.6 2336.71   849.8 2336.52
#Mann= 5 ,-1 , 0
       0      .1       0  113.89     .06       0  211.11      .1       0
   358.4    .045       0   391.9      .1       0
#XS Ineff= 2 , 0
          341.82 2324.13
Permanent Ineff=
       F       F
Bank Sta=358.4,391.9
XS Rating Curve= 0 ,0
Exp/Cntr=0.3,0.1

Type RM Length L Ch R = 1 ,4711    ,265.92,266.43,266.94
XS GIS Cut Line= 3
2122164.39479628372342.5479886982121897.72800678372375.881255358
2121353.28355762372667.547994867
#Sta/Elev= 30
       0 2312.88    73.1 2313.97   123.2 2312.75   152.5 2315.06     179 2313.34
   198.8 2315.03   221.9 2315.63   268.2 2314.69   305.4 2315.51   321.7 2312.64
   363.4 2314.49   364.9 2314.05   371.7 2308.49   376.5 2306.18   398.1 2304.56
   405.9 2305.44  410.872308.375   415.3 2311.37   420.8 2312.33   446.9 2311.44
   472.9 2312.73   480.3  2314.8   492.8 2320.94   507.4 2323.07   718.2 2325.76
   761.9 2325.56   830.2 2327.02   856.6 2327.04   877.5 2325.82   886.4 2326.37
#Mann= 7 ,-1 , 0
       0      .1       0    22.2     .06       0   151.4     .05       0
  217.23      .1       0   371.7    .045       0  410.87      .1       0
  545.86     .05       0
#XS Ineff= 2 , 0
          359.37 2316.28  423.32         2314.13
Permanent Ineff=
       F       F
Bank Sta=371.7,410.87
XS Rating Curve= 0 ,0
Exp/Cntr=0.3,0.1