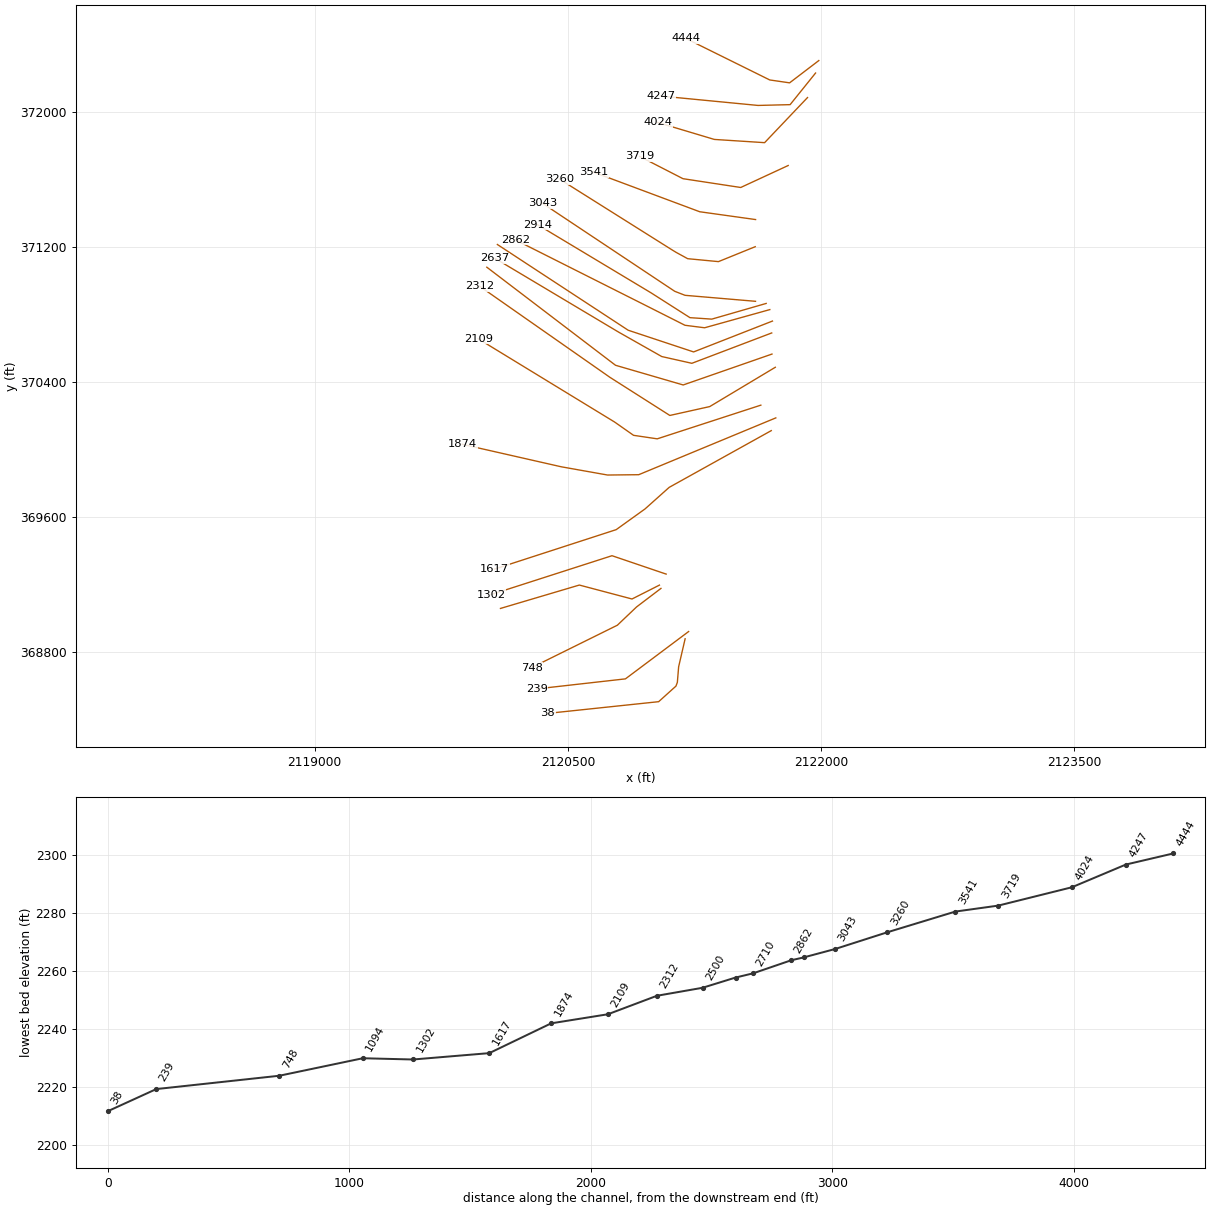
HEC-RAS study ROARINGCK.prj: ROARINGCK

--- ROARINGCK.g01 (geometry) --- (continued)

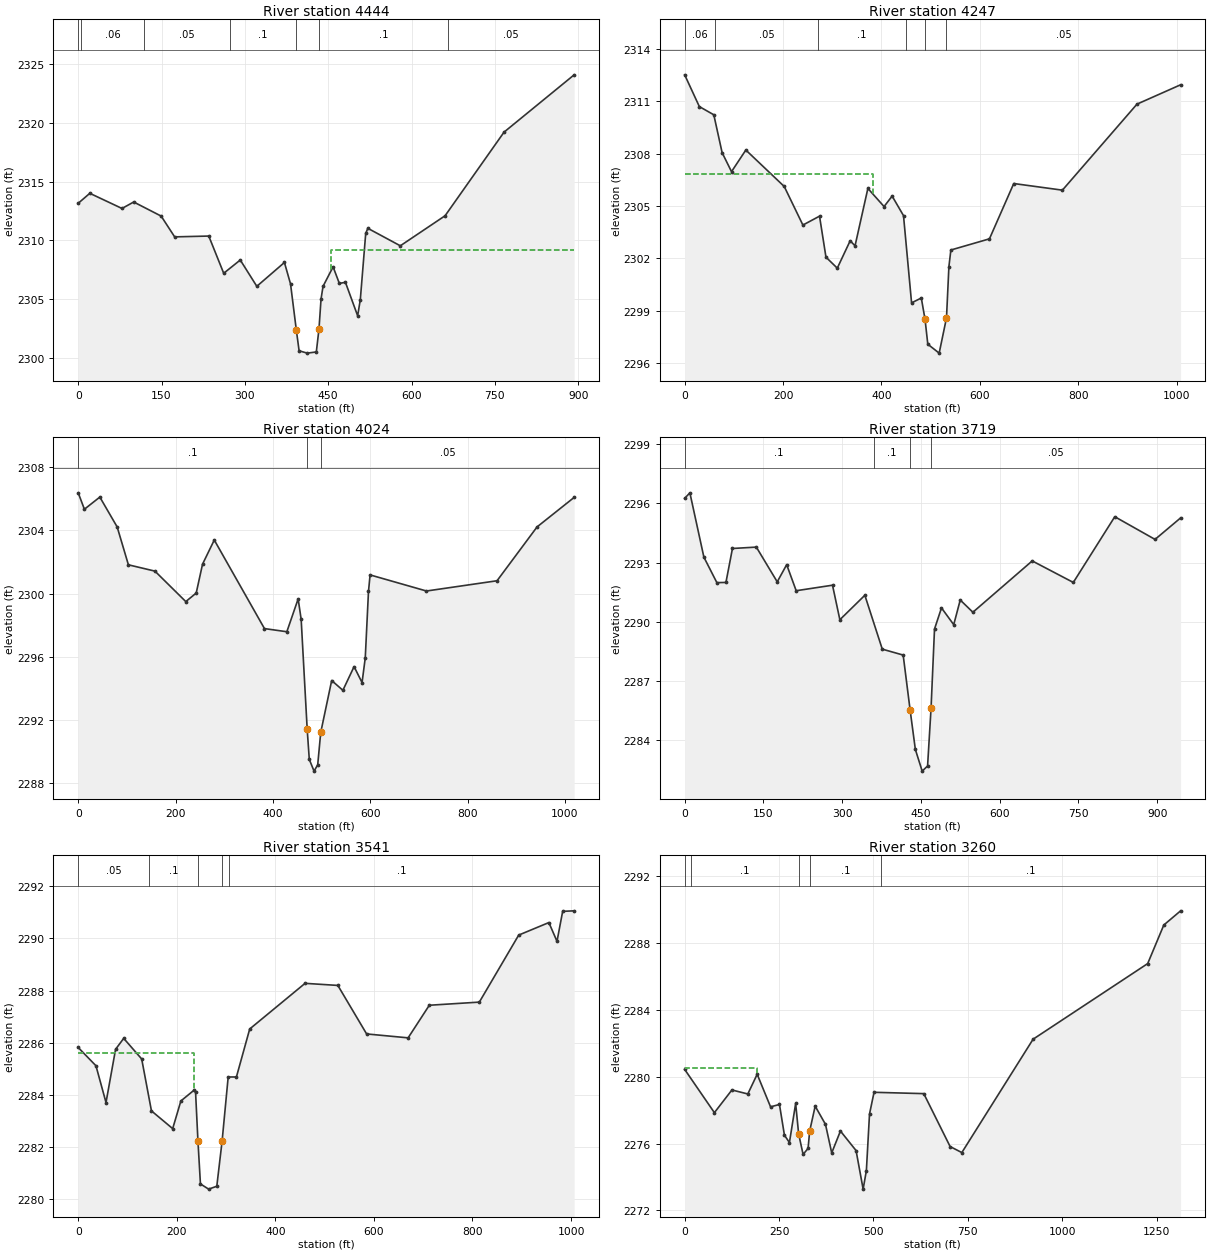
Type RM Length L Ch R = 1 ,4444    ,191.83,197.3,202.76
XS GIS Cut Line= 4
2121987.06014365372304.3864153212121813.87918392372172.310735668
 2121696.1890398372189.5282816142121197.92527255372436.056003779
#Sta/Elev= 30
       0 2313.16    20.9 2314.01    78.8 2312.72    99.9 2313.27   149.3 2312.07
   173.6  2310.3     235 2310.37   261.9  2307.2   291.7 2308.33   321.5 2306.09
   371.2 2308.12   382.2 2306.29   392.7 2302.33   397.6  2300.6   412.2  2300.4
   428.6  2300.5   433.4 2302.46   437.1 2305.01   440.7 2306.09   458.8 2307.75
     470 2306.34     481 2306.43     503 2303.58   507.8 2304.96   517.5 2310.59
   521.3 2311.03   579.8 2309.54   660.4  2312.1   766.5 2319.22   892.7  2324.1
#Mann= 7 ,-1 , 0
       0      .1       0    5.48     .06       0  118.19     .05       0
  273.27      .1       0   392.7    .045       0   433.4      .1       0
  665.73     .05       0
#XS Ineff= 2 , 0
                          455.57          2309.2
Permanent Ineff=
       F       F
Bank Sta=392.7,433.4
XS Rating Curve= 0 ,0
Exp/Cntr=0.3,0.1

Type RM Length L Ch R = 1 ,4247    ,222.66,223.22,223.79
XS GIS Cut Line= 4
2121967.72767758372230.5027783232121817.02902715 372043.16716342
2121626.74462488372038.4865889552121052.09190279372094.042252108
#Sta/Elev= 30
       0 2312.51    29.8 2310.69    59.2 2310.22    76.1 2308.05    95.2 2306.96
   124.3  2308.2   202.4 2306.11   240.3  2303.9   274.1 2304.41   287.2 2302.06
   310.2 2301.43   336.4    2303   346.3 2302.71   372.4    2306   405.3 2304.96
   421.7 2305.56   444.8 2304.44   461.2 2299.44     481 2299.72  488.61 2298.49
   494.2 2297.07   517.3 2296.56   532.2 2298.58   537.1 2301.52   541.1 2302.47
   619.5 2303.11   668.9 2306.28   767.8  2305.9   919.4 2310.83  1008.1 2311.94
#Mann= 6 ,-1 , 0
       0     .06       0   61.64     .05       0  271.27      .1       0
  449.36      .1       0  488.61    .045       0   532.2     .05       0
#XS Ineff= 2 , 0
          383.02 2306.83
Permanent Ineff=
       F       F
Bank Sta=488.61,532.2
XS Rating Curve= 0 ,0
Exp/Cntr=0.3,0.1

Type RM Length L Ch R = 1 ,4024    ,306.23,304.88,303.54
XS GIS Cut Line= 4
2121920.10002015372085.2535974662121665.83655232371817.953372793
2121368.06403989371837.0975560252121031.25861111371937.792236537
#Sta/Elev= 30
       0 2306.38    12.7 2305.34    44.4 2306.11      80 2304.22   103.1 2301.82
   157.6 2301.42     221 2299.49   242.4 2300.03   255.4 2301.86   279.5 2303.39
   382.6 2297.78   428.6 2297.58   451.8 2299.66     458 2298.37   470.4 2291.39
   474.7 2289.49   484.5 2288.75     492 2289.15   498.2  2291.2   520.7 2294.49
   543.7 2293.87   566.7 2295.37   583.1 2294.36   589.7 2295.93   596.3 2300.13
   599.6 2301.18   715.4 2300.16   860.4 2300.81   942.6 2304.22  1018.8 2306.09
#Mann= 3 ,-1 , 0
       0      .1       0   470.4    .045       0   498.2     .05       0
Bank Sta=470.4,498.2
XS Rating Curve= 0 ,0
Exp/Cntr=0.3,0.1

Type RM Length L Ch R = 1 ,3719    ,177.55,177.56,177.56
XS GIS Cut Line= 4
2121805.56414911371682.5837574452121524.31405547371552.375356451
2121182.30030379371604.4589136992120925.35560772371736.403203622
#Sta/Elev= 30
       0 2296.26     9.9 2296.54    36.6 2293.28    61.3 2291.99    78.6    2292
      91 2293.72   136.5 2293.79   176.3 2292.03   194.3  2292.9   212.4 2291.58
   281.6 2291.86   295.6 2290.11   343.2 2291.35   376.4 2288.62   416.2 2288.32
   429.5 2285.52   439.4 2283.54   452.4 2282.44   462.7  2282.7   469.3 2285.62
   475.9 2289.64   489.2 2290.71   512.5 2289.86   524.9 2291.11     549 2290.49
     662 2293.09   740.3    2292   819.3 2295.33     896 2294.18   944.7 2295.27
#Mann= 4 ,-1 , 0
       0      .1       0  359.81      .1       0   429.5    .045       0
   469.3     .05       0
Bank Sta=429.5,469.3
XS Rating Curve= 0 ,0
Exp/Cntr=0.3,0.1

Type RM Length L Ch R = 1 ,3541    ,280.67,281.51,282.35
XS GIS Cut Line= 3
2121612.38383102371362.352941501 2121281.4883621371408.605966328
2120651.75055905371643.582873389
#Sta/Elev= 30
       0 2285.82      36 2285.12    56.4 2283.71    75.8 2285.75    92.3 2286.17
   128.8 2285.38   148.6 2283.39   191.7 2282.71   208.3 2283.77   234.8 2284.18
   238.1 2284.11   242.92282.252     248 2280.59   264.6 2280.39   281.2  2280.5
   291.92282.219   304.3 2284.69     321 2284.69     348 2286.53   460.3 2288.28
   526.8  2288.2   585.2 2286.34   669.4 2286.19   712.4 2287.44   813.9 2287.56
   893.8 2290.13     955 2290.61   971.5 2289.89     983 2291.04  1006.3 2291.06
#Mann= 5 ,-1 , 0
       0     .05       0  144.23      .1       0   242.9    .045       0
   291.9      .1       0  305.17      .1       0
#XS Ineff= 2 , 0
          234.97 2285.59
Permanent Ineff=
       F       F
Bank Sta=242.9,291.9
XS Rating Curve= 0 ,0
Exp/Cntr=0.3,0.1

Type RM Length L Ch R = 1 ,3260    ,216.47,216.62,216.76
XS GIS Cut Line= 6
2121610.29096657371201.5054269712121392.36976555371113.139358282
2121210.07780731371130.5005440262121141.96062954371167.767623733
2121120.17730092371180.9781355592120449.80440633371602.698513242
#Sta/Elev= 30
       0 2280.44    78.7 2277.85   125.1 2279.21   167.2 2278.97     192 2280.15
   227.4  2278.2     251 2278.34   264.2  2276.5   277.4 2276.06   293.9  2278.4
   301.8 2276.58   313.6 2275.35   326.8 2275.71     3312276.743   345.6 2278.24
   372.9 2277.15   389.4 2275.44   412.5 2276.75   453.9 2275.58   472.6 2273.27
   481.2 2274.38   489.5 2277.77   501.5 2279.07   633.2 2278.99     703 2275.82
     734 2275.46   922.7 2282.25  1226.2 2286.78  1268.9 2289.09  1313.4 2289.94
#Mann= 5 ,-1 , 0
       0     .06       0   17.45      .1       0   301.8    .045       0
     331      .1       0  520.95      .1       0
#XS Ineff= 2 , 0
          190.83 2280.54
Permanent Ineff=
       F       F
Bank Sta=301.8,331
XS Rating Curve= 0 ,0
Exp/Cntr=0.3,0.1

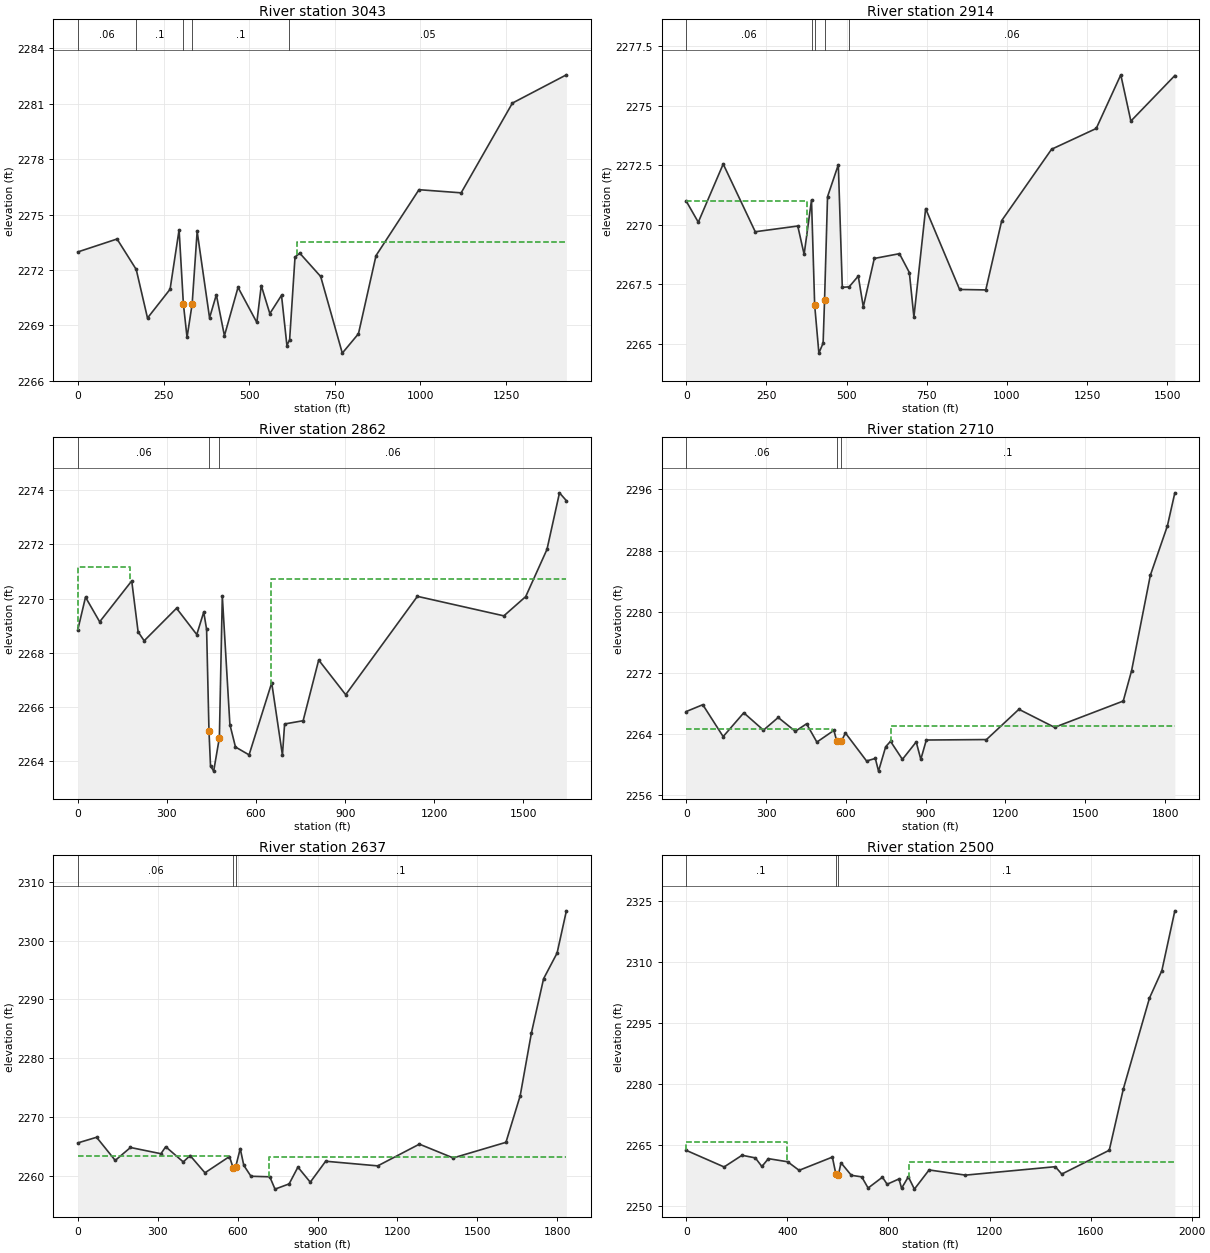
Type RM Length L Ch R = 1 ,3043    ,129.28,129.55,129.83
XS GIS Cut Line= 4
2121611.99317657 370878.006984842121194.45283854370913.486542359
2121133.38789838370937.2564079342120349.79928417371458.688726547
#Sta/Elev= 30
       0 2272.98   114.4 2273.68   170.4 2272.03   203.3  2269.4   269.2 2270.96
   295.5 2274.18     308 2270.17   318.7 2268.35   333.6 2270.16   348.2 2274.09
   384.4 2269.41   404.2 2270.66   427.8 2268.44   467.5 2271.06   522.4 2269.16
   535.3 2271.16   560.3 2269.64   594.4 2270.63   610.2 2267.91   618.1 2268.23
   633.8  2272.7   647.8 2272.91   708.7 2271.65   771.8  2267.5     819 2268.55
   870.2 2272.78   995.6 2276.35  1118.7 2276.18  1268.3 2281.04  1425.8 2282.57
#Mann= 5 ,-1 , 0
       0     .06       0   170.4      .1       0     308    .045       0
   333.6      .1       0   617.5     .05       0
#XS Ineff= 2 , 0
                          640.18         2273.51
Permanent Ineff=
       F       F
Bank Sta=308,333.6
XS Rating Curve= 0 ,0
Exp/Cntr=0.5,0.3

Type RM Length L Ch R = 1 ,2914    ,52.45,51.99,56.99
XS GIS Cut Line= 5
2121674.99420029370865.3094733662121352.94530371370772.427441284
2121223.60501119370781.108198196 2120992.9207971370928.257473052
2120320.00613448371332.283626726
#Sta/Elev= 30
       0 2270.99    37.4 2270.11   115.1 2272.55     215 2269.71   347.6 2269.95
   367.4 2268.76   390.4 2271.04   400.3 2266.63   413.4 2264.62   426.6 2265.04
   431.1 2266.84   440.4 2271.18     474 2272.52   486.4 2267.38   507.8  2267.4
   536.2 2267.85   551.9 2266.56   586.2 2268.59   664.6 2268.79   695.5    2268
   709.7 2266.13   746.3 2270.68   852.2 2267.29   933.8 2267.27   983.6 2270.18
    1139 2273.17  1278.2 2274.04  1354.8 2276.29  1386.2 2274.35  1523.3 2276.26
#Mann= 5 ,-1 , 0
       0     .06       0   390.4      .1       0   400.3    .045       0
   431.1      .1       0   507.8     .06       0
#XS Ineff= 2 ,-1
       0   375.3    2271   456.1    1400    2271
Permanent Ineff=
       F       F
Bank Sta=400.3,431.1
XS Rating Curve= 0 ,0
Exp/Cntr=0.5,0.3

Type RM Length L Ch R = 1 ,2862    ,157.7,157.7,157.7
XS GIS Cut Line= 5
2121696.69527239370828.8512129492121310.41061187370721.212320611
2121194.09129071370735.969180867  2120948.112169370860.148358334
2120187.90597968371242.595837526
#Sta/Elev= 30
       0 2268.85    25.8 2270.05    73.5 2269.14   181.4 2270.65   202.9 2268.77
   223.3 2268.44   332.3 2269.64   400.4 2268.67   423.9  2269.5   433.5 2268.86
   441.52265.113   446.7 2263.82   457.3 2263.63   476.5 2264.86   486.4 2270.09
   511.9 2265.35   530.7 2264.52   576.5 2264.23   652.7 2266.89   688.8 2264.22
   696.1 2265.37   758.5 2265.49   810.9 2267.73   901.8 2266.45  1143.2 2270.08
  1434.3 2269.36  1507.8 2270.07  1579.4 2271.81  1621.6  2273.9  1644.8 2273.61
#Mann= 3 , 0 , 0
       0     .06       0   441.5    .045       0   476.5     .06       0
#XS Ineff= 2 , 0
          177.25 2271.15  650.84         2270.72
Permanent Ineff=
       F       F
Bank Sta=441.5,476.5
XS Rating Curve= 0 ,0
Exp/Cntr=0.5,0.3

Type RM Length L Ch R = 1 ,2710    ,72.5,72.5,72.5
XS GIS Cut Line= 4
2121712.31039219370760.9373817172121245.17490888370578.086680982
2120857.58396599 370706.618780972120082.48431705371214.587312609
#Sta/Elev= 30
       0 2266.94      62 2267.83   138.6 2263.66   216.1 2266.77   290.1  2264.5
   345.6 2266.16   409.8 2264.35   452.1 2265.33   490.9 2262.94   554.9 2264.47
   565.6 2263.08  582.982263.035   598.2 2264.13   677.7 2260.47   710.7  2260.8
   722.7 2259.14   749.6 2262.33   767.8 2263.04   812.5 2260.68   864.4 2262.96
   881.7 2260.68   902.4 2263.21  1128.5 2263.27  1250.5 2267.23  1384.4 2264.87
  1642.8 2268.31  1674.1 2272.28  1744.6 2284.76  1808.6 2291.21  1836.7 2295.55
#Mann= 3 , 0 , 0
       0     .06       0   565.6    .045       0  582.98      .1       0
#XS Ineff= 2 , 0
          547.82 2264.61  769.93         2265.02
Permanent Ineff=
       F       F
Bank Sta=565.6,582.98
XS Rating Curve= 0 ,0
Exp/Cntr(USF)=0,0
Exp/Cntr=0.3,0.1

Type RM Length L Ch R = 1 ,2637    ,136.8,136.8,136.8
XS GIS Cut Line= 5
2121707.93681319370690.5212136222121234.72881559370510.694079964
2121056.42813243 370550.714350022120800.00267437370695.965492583
 2120069.5074147371131.832626699
#Sta/Elev= 30
       0 2265.56    70.4 2266.52   140.4 2262.58   197.6 2264.78     312 2263.72
   329.9 2264.91   395.9 2262.32   421.4 2263.41   477.3 2260.47   569.3 2263.24
   582.8 2261.34   592.8 2261.51   609.7 2264.59   623.1 2261.74     650 2259.88
   720.7 2259.79   740.3 2257.69   793.3 2258.58   826.3 2261.44   872.7 2258.87
   930.5 2262.44    1126 2261.65  1282.4 2265.35  1409.4    2263  1607.4 2265.66
  1660.9  2273.6  1702.9 2284.26  1748.7 2293.52  1799.4 2297.89  1834.3 2305.08
#Mann= 3 , 0 , 0
       0     .06       0   582.8    .045       0   592.8      .1       0
#XS Ineff= 2 , 0
          570.46 2263.34  717.86          2263.2
Permanent Ineff=
       F       F
Bank Sta=582.8,592.8
XS Rating Curve= 0 ,0
Exp/Cntr(USF)=0,0
Exp/Cntr=0.3,0.1

Type RM Length L Ch R = 1 ,2500    ,188.8,188.8,188.8
XS GIS Cut Line= 4
 2121709.5818289370565.442840085 2121183.5443958370382.366869703
2120782.50287503370499.0333030372120020.05637318371080.020248655
#Sta/Elev= 30
       0 2263.69   149.6 2259.62   220.6 2262.49   273.3 2261.84   299.1 2259.73
   324.8 2261.66   401.2 2260.89   446.4 2258.79     578 2262.04   591.7 2257.94
     602 2257.73   612.2 2260.64     653 2257.57   694.2 2257.18   719.5 2254.44
   776.2 2257.11   794.7 2255.37   841.7 2256.67   851.9 2254.38   878.7  2257.2
   902.6 2254.17   960.7 2258.88  1104.8 2257.61  1460.1 2259.68  1485.8 2257.87
  1673.7 2263.72  1729.2 2278.74  1832.9 2301.12  1881.8 2307.85  1933.2 2322.55
#Mann= 3 , 0 , 0
       0      .1       0   591.7    .045       0     602      .1       0
#XS Ineff= 2 , 0
          398.42 2265.78  880.99         2260.85
Permanent Ineff=
       F       F
Bank Sta=591.7,602
XS Rating Curve= 0 ,0
Exp/Cntr=0.3,0.1

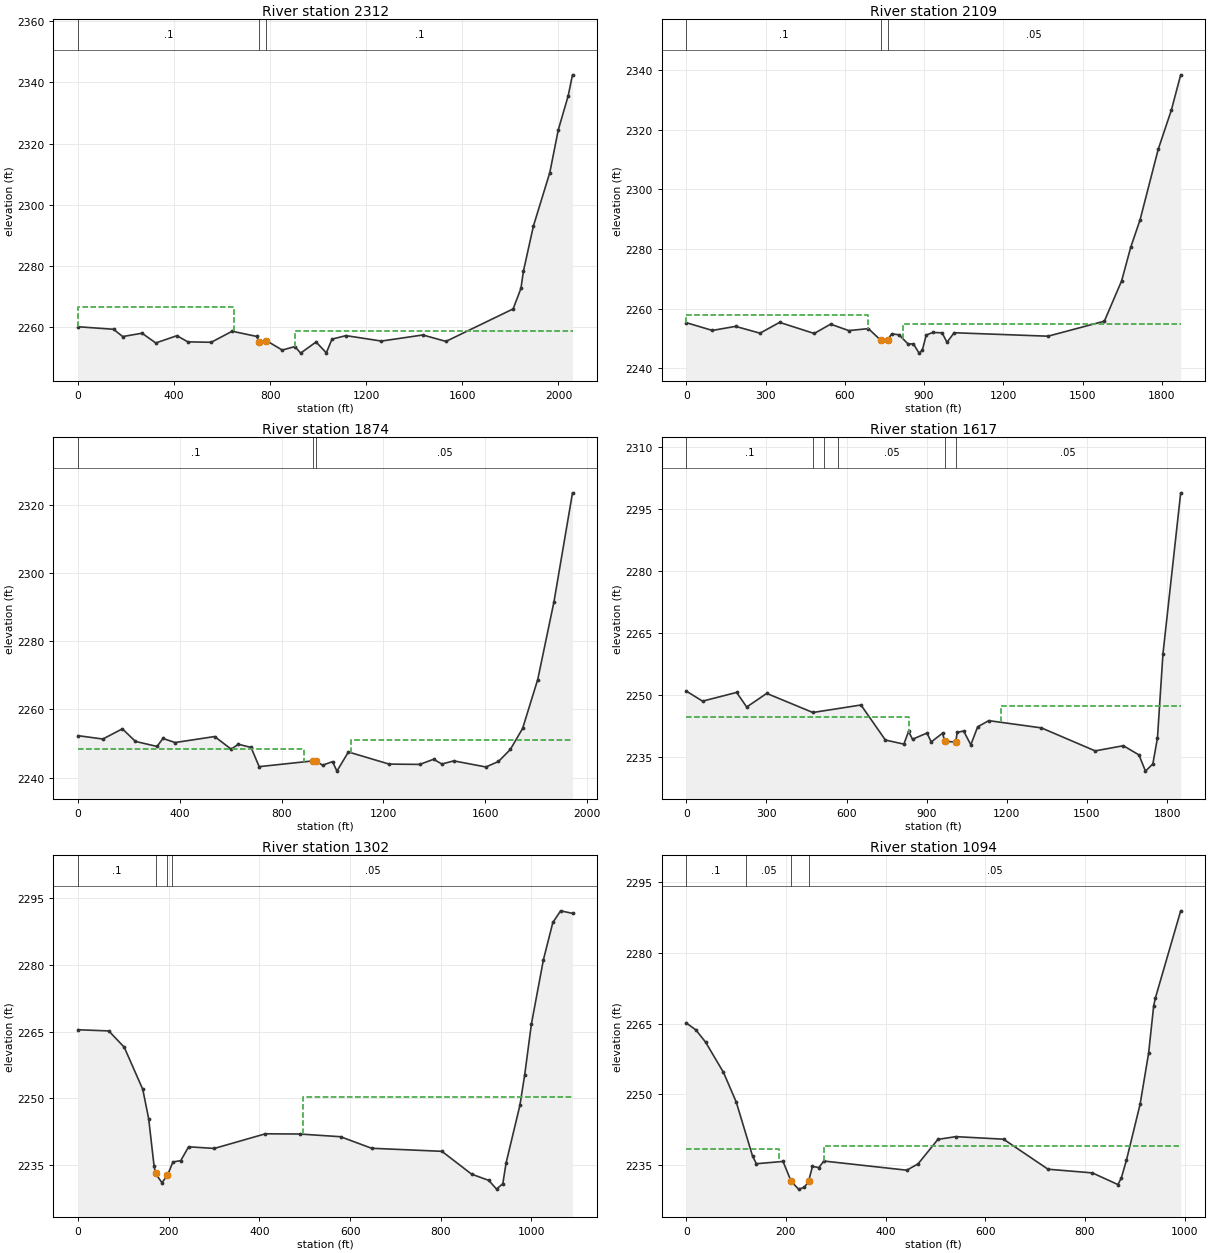
Type RM Length L Ch R = 1 ,2312    ,203,203,203
XS GIS Cut Line= 5
2121729.35778678370487.171883644 2121340.8197277370254.334524666
2121104.38988959370201.7151594932120749.50555501370427.550645137
2119976.82557198370967.763465561
#Sta/Elev= 30
       0 2260.05   147.3 2259.23   185.6 2256.84   265.9 2257.94   323.3 2254.75
   411.3 2257.12   456.7 2255.11   554.2 2254.97   641.5 2258.59   743.5 2256.88
     753 2255.15   783.9 2255.51   849.8 2252.42   902.7 2253.57   926.5 2251.42
   990.7 2255.06  1033.6 2251.51    1057    2256  1115.3 2257.15  1262.7 2255.37
  1435.5 2257.36  1531.6 2255.26  1811.3 2265.89  1843.9 2272.61    1854 2278.17
  1895.9 2293.05    1964 2310.48  1999.2 2324.44  2040.4 2335.57  2058.6  2342.5
#Mann= 3 , 0 , 0
       0      .1       0     753    .045       0   783.9      .1       0
#XS Ineff= 2 , 0
          647.37 2266.62  901.44         2258.53
Permanent Ineff=
       F       F
Bank Sta=753,783.9
XS Rating Curve= 0 ,0
Exp/Cntr(USF)=0,0
Exp/Cntr=0.3,0.1

Type RM Length L Ch R = 1 ,2109    ,232.5,234.69,236.88
XS GIS Cut Line= 5
2121643.42102443 370262.721877622121029.65559596370063.165408358
2120889.37766129370083.998700038 2120777.5918132 370162.43688199
2119968.52449453370656.304857272
#Sta/Elev= 30
       0 2255.27    98.6 2252.67   186.5 2254.04   278.9 2251.75   353.2 2255.38
   484.1 2251.65   546.2 2254.78   615.2 2252.62   689.4 2253.28   735.8  2249.4
   762.3  2249.5   777.6 2251.53   805.4 2251.21   839.7 2248.11   859.5 2248.18
   881.4 2245.06   893.4 2245.99   908.2 2251.12   933.1 2251.99   968.4 2251.88
   986.9 2248.69    1014  2251.9  1369.4 2250.74  1582.7 2255.78    1648  2269.3
  1682.6 2280.61  1717.9 2289.78  1786.4 2313.38  1836.4 2326.61  1871.7 2338.42
#Mann= 3 , 0 , 0
       0      .1       0   735.8    .045       0   762.3     .05       0
#XS Ineff= 2 , 0
          687.35 2257.88  820.67         2254.85
Permanent Ineff=
       F       F
Bank Sta=735.8,762.3
XS Rating Curve= 0 ,0
Exp/Cntr=0.3,0.1

Type RM Length L Ch R = 1 ,1874    ,246.78,256.26,265.58
XS GIS Cut Line= 5
2121732.16511986370187.2661256012120919.93337446369850.665505275
2120735.15520827369848.7446083182120460.59429523369897.659026659
2119875.22129561370030.650526365
#Sta/Elev= 30
       0 2252.32    97.2 2251.34   173.9 2254.33   225.1 2250.65   310.3 2249.16
   333.1 2251.51   381.3 2250.31   536.5 2252.07   601.5 2248.38   629.9 2249.81
   679.6 2248.88   711.6 2243.25   921.2 2244.92     936 2244.84   960.6 2243.68
    1000 2244.72  1017.2 2241.94  1062.3 2247.55  1222.3    2244  1342.9 2243.91
  1397.1 2245.41  1429.7 2244.03  1476.6 2244.94  1602.8 2243.16  1652.1 2244.76
  1698.7 2248.28    1747 2254.43  1806.5 2268.77  1870.4 2291.57  1943.2 2323.44
#Mann= 3 , 0 , 0
       0      .1       0   921.2    .045       0     936     .05       0
#XS Ineff= 2 , 0
          886.02 2248.33 1073.99         2250.93
Permanent Ineff=
       F       F
Bank Sta=921.2,936
XS Rating Curve= 0 ,0
Exp/Cntr=0.3,0.1

Type RM Length L Ch R = 1 ,1617    ,329.95,315.39,300.99
XS GIS Cut Line= 5
2121705.32261221370111.8345052462121100.48878762369775.665327191
2120957.43329945369647.8876956112120786.51567432 369525.15428105
2120066.74168126 369291.62688881
#Sta/Elev= 30
       0 2251.03    60.8  2248.6   188.4 2250.71     226 2247.18     301 2250.47
   473.7 2245.86   653.9 2247.67   745.3  2239.2   814.5 2238.22   832.1 2241.29
   846.9 2239.39   900.9 2240.89     917 2238.75   959.3 2240.86   967.5 2238.93
  1008.7  2238.7    1014 2241.05  1038.2 2241.39  1065.1 2238.05  1090.8  2242.4
  1132.3 2243.89  1329.3 2242.14  1530.7 2236.58  1636.2 2237.83  1694.6 2235.61
    1719 2231.69  1746.6 2233.43  1763.9  2239.7  1784.5 2260.04  1850.9 2298.94
#Mann= 6 ,-1 , 0
       0      .1       0  473.14    .045       0   514.2      .1       0
  569.74     .05       0   967.5    .045       0  1008.7     .05       0
#XS Ineff= 2 , 0
          834.81 2244.81    1179         2247.38
Permanent Ineff=
       F       F
Bank Sta=967.5,1008.7
XS Rating Curve= 0 ,0
Exp/Cntr=0.3,0.1

Type RM Length L Ch R = 1 ,1302    ,207.18,208.3,209.41
XS GIS Cut Line= 3
2121082.43337753369261.7765911972120761.70827609369370.709560155
2120045.92583363369140.596650238
#Sta/Elev= 30
       0 2265.42    67.6 2265.15   101.7 2261.48   142.6 2251.98   155.6 2245.37
   167.5 2234.73   170.7 2233.05   184.8 2230.95     197 2232.58   209.1 2235.62
   226.4 2235.92   243.7 2239.04   300.4 2238.67   413.1 2241.97   488.9 2241.92
   578.9 2241.31   647.4 2238.71   802.5 2238.02   868.1 2232.87   905.9 2231.47
   923.1  2229.5   936.9 2230.74     944 2235.36   974.5 2248.37   985.2 2255.32
   999.9  2266.7  1026.5 2281.23  1047.2 2289.59  1064.4 2292.22  1090.6 2291.65
#Mann= 4 ,-1 , 0
       0      .1       0   170.7    .045       0     197      .1       0
  207.79     .05       0
#XS Ineff= 2 , 0
                          496.43         2250.15
Permanent Ineff=
       F       F
Bank Sta=170.7,197
XS Rating Curve= 0 ,0
Exp/Cntr=0.3,0.1

Type RM Length L Ch R = 1 ,1094    ,334.1,345.65,357.2
XS GIS Cut Line= 4
2121042.72249895 369196.556577282120880.22249588369114.264747113
2120568.13500268369196.8520831112120100.94971307369058.330849401
#Sta/Elev= 30
       0 2265.13    19.3 2263.65    38.6 2261.08    74.6 2254.66   100.2 2248.38
     133 2236.91   140.6 2235.31   194.1  2235.8   210.42231.583   225.3 2229.93
   237.1  2230.3   245.52231.657   253.2 2234.74     266  2234.5   276.2 2235.88
   442.5 2233.94   465.2 2235.29     505 2240.47   541.2 2241.05   636.7 2240.51
     726 2234.15     815 2233.37   866.3  2230.9   873.1 2232.28   883.4 2236.06
   910.8 2247.91   927.9 2258.74   938.1 2268.77   941.6 2270.46   992.3 2288.89
#Mann= 4 ,-1 , 0
       0      .1       0  119.13     .05       0   210.4    .045       0
   245.5     .05       0
#XS Ineff= 2 , 0
          185.06 2238.47  277.31         2239.08
Permanent Ineff=
       F       F
Bank Sta=210.4,245.5
XS Rating Curve= 0 ,0
Exp/Cntr=0.3,0.1

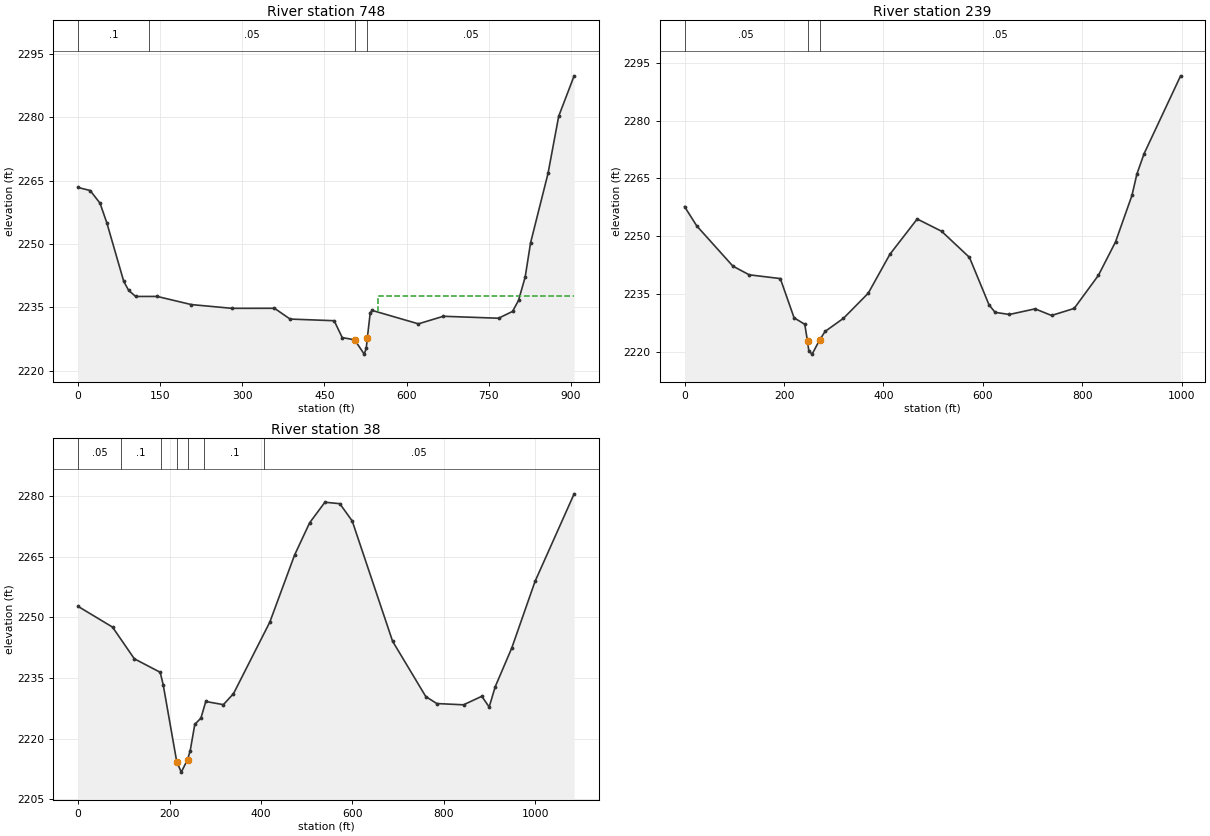
Type RM Length L Ch R = 1 ,748     ,505.78,509.35,512.38
XS GIS Cut Line= 4
2121051.87766439369177.0543196952120907.43339947369067.332098201
2120793.54451963368958.9986534422120284.90911095368707.468074177
#Sta/Elev= 30
       0 2263.36      22 2262.64      40 2259.65    52.5 2254.98    83.4 2241.12
    92.3 2239.01   105.1 2237.56   144.3 2237.57   206.8 2235.64     281 2234.75
   358.7 2234.76   387.2 2232.21   467.7 2231.82   482.4 2227.83     5052227.299
   522.6 2223.91   526.3 2225.32  528.352227.844   533.6 2233.73   537.3 2234.25
   621.5 2231.08   667.2 2232.87   767.9 2232.41   793.5 2234.02   804.4 2236.62
   816.6 2242.19   826.4 2250.25   858.3  2266.7   877.8 2280.24     906 2289.79
#Mann= 4 ,-1 , 0
       0      .1       0  129.79     .05       0     505    .045       0
  528.35     .05       0
#XS Ineff= 2 , 0
                          547.82         2237.68
Permanent Ineff=
       F       F
Bank Sta=505,528.35
XS Rating Curve= 0 ,0
Exp/Cntr=0.3,0.1

Type RM Length L Ch R = 1 ,239     ,187.78,200.78,214.32
XS GIS Cut Line= 3
 2121215.7667723368921.4987284542120841.25620912368641.032043958
2120314.75297265368581.576427185
#Sta/Elev= 30
       0 2257.67    24.5 2252.66    97.2  2242.2     130 2239.94   192.6 2238.96
   220.3 2228.76   241.8 2227.07   247.32222.649     250 2220.09   256.6 2219.32
  271.532222.978   282.7 2225.23   319.6 2228.63   369.4 2235.15   413.1  2245.3
   467.9 2254.45   516.9 2251.27     573 2244.47   612.4 2232.13   624.6 2230.18
   653.4 2229.63     705 2231.09   738.1 2229.37   783.6  2231.2   832.3 2239.79
   866.8  2248.5   899.8 2260.57   909.8 2266.15   924.2 2271.42   997.7 2291.67
#Mann= 3 ,-1 , 0
       0     .05       0   247.3    .045       0  271.53     .05       0
Bank Sta=247.3,271.53
XS Rating Curve= 0 ,0
Exp/Cntr=0.3,0.1

Type RM Length L Ch R = 1 ,38      ,28.19,38.3,48.42
XS GIS Cut Line= 6
2121194.93315256368878.4430402822121156.50737637368712.702230036
2121148.86861214368620.3411942872121140.53529546368598.119125858
2121038.13076906368505.8992099182120381.44938837368436.578729735
#Sta/Elev= 30
       0 2252.74    75.3 2247.61     123 2239.76   179.5 2236.43   186.1 2233.34
   215.7 2214.29   225.6  2211.7   239.3 2214.78   245.2 2217.05   255.2 2223.53
   268.6 2225.08   279.2 2229.19   317.7 2228.41   339.8 2231.13   419.2 2248.84
   473.3 2265.43   506.3 2273.44   539.7 2278.53   572.3 2278.17   599.4 2273.89
   687.7 2244.11   760.3 2230.41   784.4 2228.68   842.8 2228.37   882.8 2230.48
   898.9 2227.82   912.1 2232.85   948.4 2242.47   999.2 2258.93  1084.7 2280.61
#Mann= 7 ,-1 , 0
       0     .05       0   94.81      .1       0  180.78     .05       0
   215.7    .045       0   239.3     .05       0  276.22      .1       0
  407.25     .05       0
Bank Sta=215.7,239.3
XS Rating Curve= 0 ,0
Exp/Cntr=0.3,0.1
LCMann Table=0

Chan Stop Cuts=-1
Use User Specified Reach Order=0
Composite Channel Slope=5